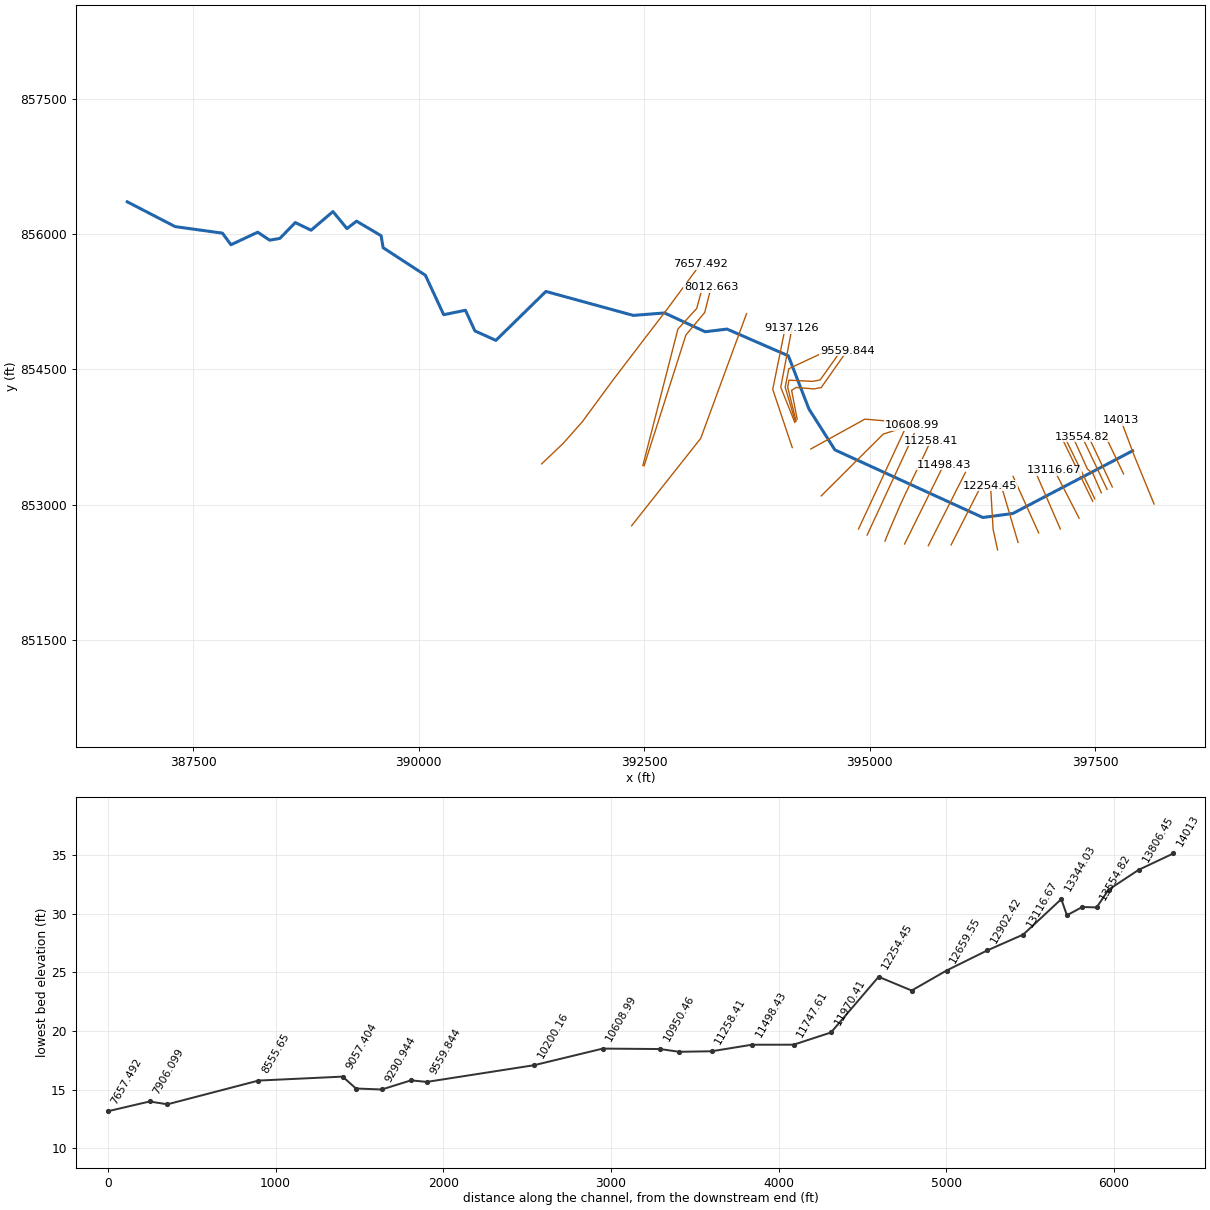
--- 6977_ras.prj (project) ---

Proj Title=6977
Current Plan=p01
Default Exp/Contr=0.3,0.1
English Units
Geom File=g01
Flow File=f01
Plan File=p01
Y Axis Title=Elevation
X Axis Title(PF)=Main Channel Distance
X Axis Title(XS)=Station
BEGIN DESCRIPTION:
RFD model 6977 exported to HEC-RAS
END DESCRIPTION:

--- 6977_ras.p01 (plan) ---

Plan Title=Plan 01
Program Version=4.10
Short Identifier=Plan 01
Geom File=g01
Flow File=f01
Subcritical Flow
Calc Critical at every XS
Secant Critical Depth

--- 6977_ras.f01 (steady flow) ---

Flow Title=Flow 01
Program Version=5.01
Number of Profiles= 6
Profile Names=10yr,25yr,50yr,100yr,100plus,500yr
River Rch & RM=6977,42,   14013
  236.37   376.5  506.92  625.12  912.68  1504.8
River Rch & RM=6977,42,13806.45
  257.48  410.47  552.99  682.23  996.06 1623.51
River Rch & RM=6977,42,13626.62
  268.72  428.52  577.45  712.52 1040.28 1685.72
River Rch & RM=6977,42, 13469.3
  272.82  435.11  586.37  723.57 1056.41  1708.3
River Rch & RM=6977,42,13344.03
  295.82   472.3  637.01  786.52 1148.31 1837.47
River Rch & RM=6977,42,13116.67
  365.03  583.28  787.24  972.33  1419.6 2205.59
River Rch & RM=6977,42,12902.42
  372.16  594.83  802.98  991.91 1448.19 2244.35
River Rch & RM=6977,42,12659.55
  379.94  607.43  820.16 1013.28 1479.39  2286.5
River Rch & RM=6977,42,12451.69
  382.97  612.35  826.86 1021.61 1491.56 2302.92
River Rch & RM=6977,42,12254.45
  392.82  628.25   848.5 1048.49 1530.79 2355.49
River Rch & RM=6977,42,11970.41
  429.08  686.68  927.87 1146.92  1674.5 2545.65
River Rch & RM=6977,42,11747.61
   438.3  701.61   948.2 1172.21 1711.43 2594.49
River Rch & RM=6977,42,11498.43
  445.79  713.75  964.78 1192.85 1741.56 2634.34
River Rch & RM=6977,42,11258.41
  476.63  763.85 1033.19 1278.09 1866.01 2798.19
River Rch & RM=6977,42,11064.59
  480.68  770.47 1042.26 1289.44 1882.58 2820.09
River Rch & RM=6977,42,10950.46
  481.61  771.99 1044.36 1292.05  1886.4 2825.13
River Rch & RM=6977,42,10608.99
  510.37  819.01 1108.82 1372.66 2004.08 2979.78
River Rch & RM=6977,42,10200.16
  519.56  834.04 1129.43 1398.44 2041.72 3028.99
River Rch & RM=6977,42,9559.844
  697.61 1124.77 1527.91 1896.37  2768.7 3954.39
River Rch & RM=6977,42,9290.944
  718.91 1159.95 1576.49 1957.47 2857.91 4067.15
River Rch & RM=6977,42,9137.126
  719.72  1161.3 1578.36 1959.83 2861.35 4071.52
River Rch & RM=6977,42,9057.404
  721.63 1164.47 1582.74 1965.35 2869.41 4081.71
River Rch & RM=6977,42, 8555.65
  744.97 1203.14 1636.25 2032.77 2967.85 4206.05
River Rch & RM=6977,42,8012.663
  758.38 1225.41  1667.1 2071.68 3024.65 4277.68
River Rch & RM=6977,42,7906.099
  784.12 1268.07 1726.14 2146.09 3133.29 4413.91
River Rch & RM=6977,42,7657.492
  787.85 1274.26 1734.71 2156.89 3149.05 4433.64
River Rch & RM=6977,42,7164.657
   800.1 1294.82 1763.38 2193.26 3202.16 4501.02
River Rch & RM=6977,42,6550.609
     810 1311.43 1786.56 2222.69 3245.13 4555.48
River Rch & RM=6977,42,6320.623
  858.44 1393.68 1902.11 2370.22 3460.52 4830.85
River Rch & RM=6977,42,5017.381
  863.32 1401.93 1913.66 2384.94 3482.02 4858.05
River Rch & RM=6977,42,4749.817
   863.8 1402.75 1914.81  2386.4 3484.15 4860.76
River Rch & RM=6977,42,4092.464
  863.32 1401.93 1913.66 2384.94 3482.02 4858.05
Boundary for River Rch & Prof#=6977,42,1
Up Type= 0
Dn Type= 2
Boundary for River Rch & Prof#=6977,42,2
Up Type= 0
Dn Type= 2
Boundary for River Rch & Prof#=6977,42,2
Up Type= 0
Dn Type= 2
Boundary for River Rch & Prof#=6977,42,2
Up Type= 0
Dn Type= 2
Boundary for River Rch & Prof#=6977,42,2
Up Type= 0
Dn Type= 2
Boundary for River Rch & Prof#=6977,42,2
Up Type= 0
Dn Type= 2

--- 6977_ras.g01 (geometry) ---

Geom Title=6977
Program Version=4.10

River Reach=6977,42
Reach XY= 30
397915.594438761 853596.11050573396589.639577895852901.666061312
396256.306244314852856.527172416394616.028466642853606.787589073
394327.834022164 854060.78064464 394099.39073506854650.841408551
393420.137262851854947.065366879393177.081707418854917.768491864
392726.777887851855126.101825163 392380.64073512855098.975089088
391411.673721164855364.817102939390857.219973117 854822.06010814
390624.425586045854926.914150745 390519.56447494855156.080817401
 390278.59225297855106.775261894390075.554058254855544.275261879
389606.804058254855850.264845192389584.668641806855983.077345192
 389312.53322494856144.535678521389205.762391597856062.504428536
   389050.814475856251.306511849 388808.62697494856044.275261864
388632.845725149856128.910678551388462.272808254855953.129428566
388348.991558254855933.598178521388216.179058462856022.139845222
387920.381170541855882.853459165 387825.03322494856011.636372998
387301.563860565856084.170371816386770.138274103856359.122339427

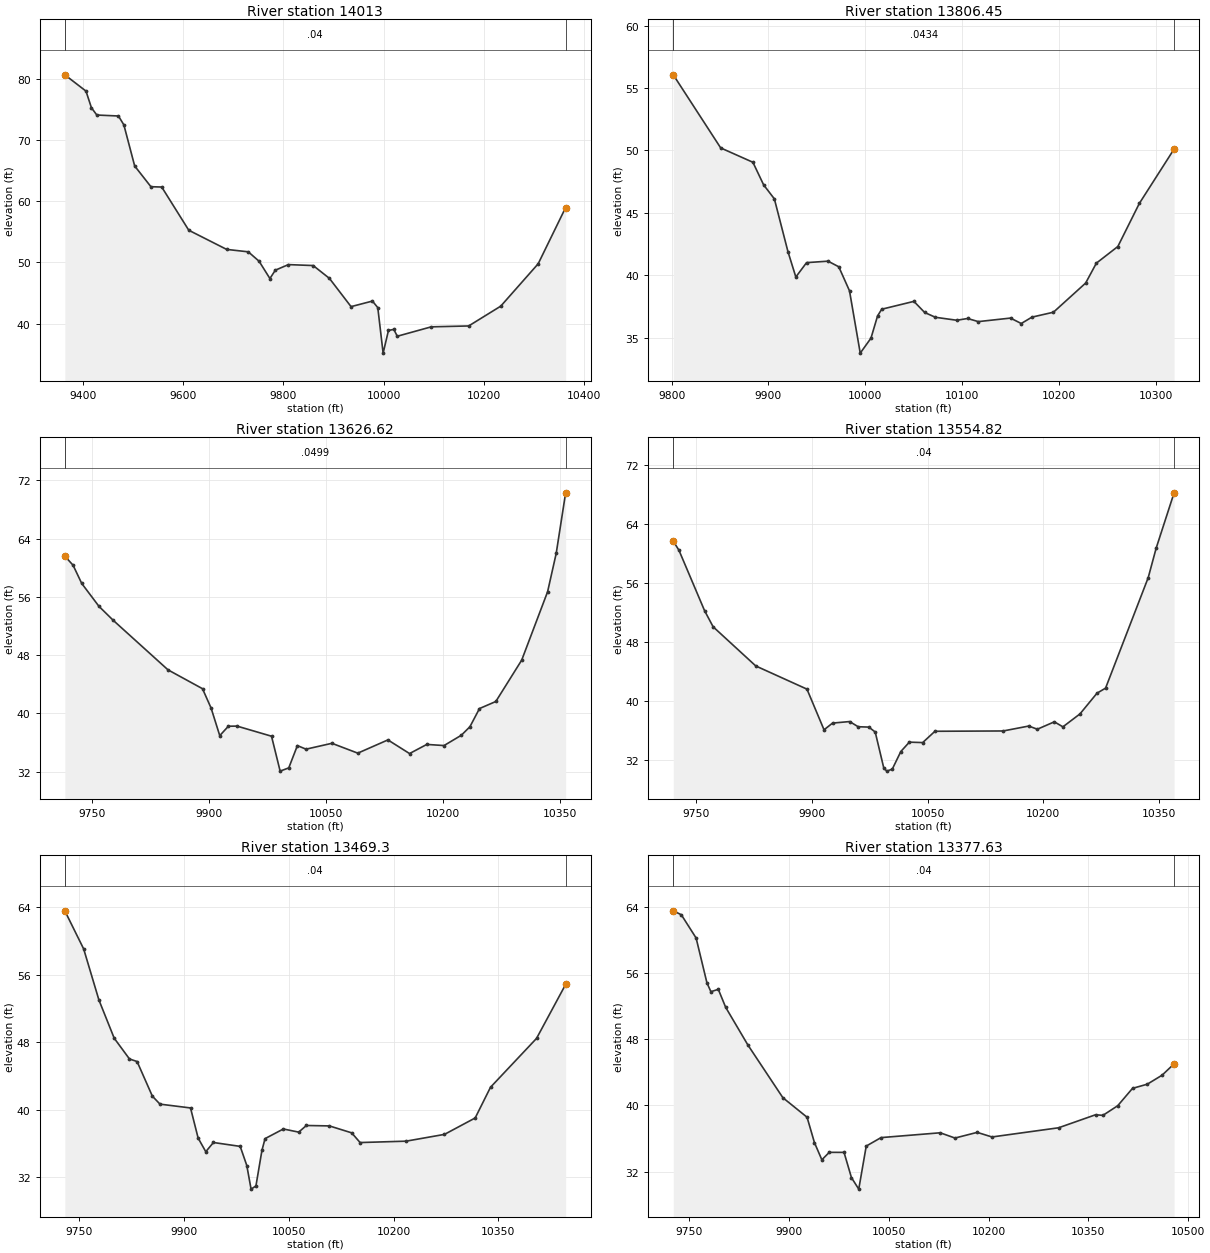
Type RM Length L Ch R = 1 ,   14013,206.557700,206.557700,206.557700
XS GIS Cut Line= 6
 398154.58898067853005.875169056 398050.76127341853258.896932657
397935.719188142853539.247448631397914.980930832853594.836296953
397914.320229981853596.724013666397786.434322072853936.322451619
#Sta/Elev= 30
9363.13680.687289405.42778.021469416.23675.309519427.04574.109269470.28273.95152
9481.09172.50065 9502.7165.772959535.13762.383049556.75662.328799610.80255.25999
9686.46652.125879729.70351.726679751.32150.18948 9772.9447.358249783.749 48.7236
9809.85649.636569859.41349.483819891.84147.385049935.07842.759959977.82843.67302
9988.50142.596129999.173 35.154210009.8438.8663410020.5339.0383210027.4537.91618
10095.3339.4557110170.1339.5997410234.2442.8422310309.04 49.776310363.8858.97527
#Mann= 3 , 0 , 0
9363.136    0.04       09363.136    0.04       010363.88    0.04       0
#XS Ineff= 2 , 0
       09954.381                       0
Bank Sta=9363.136,10363.88
Exp/Cntr=0.3,0.1

Type RM Length L Ch R = 1 ,13806.45,179.827600,179.827600,179.827600
XS GIS Cut Line= 2
397816.175218607853340.819259797397592.650913058853807.399120895
#Sta/Elev= 30
9801.733 56.05269850.72250.196799883.98749.048169895.07547.237369906.16446.11527
9920.18141.89425 9928.3439.857459939.42841.008229961.605 41.12539972.69340.67634
9983.782 38.7497 9994.8733.7590610005.9634.9582110012.7636.7365210017.0537.27592
10050.31 37.9053 10061.437.0165110072.4936.6305410094.6636.3915510105.75 36.5333
10116.8436.2837510150.1136.5669210161.1936.1315810172.28 36.642810194.4637.03639
10227.72 39.371510238.8140.9665310260.9942.2995710283.1745.7474710319.0950.10554
#Mann= 3 , 0 , 0
9801.733  0.0434       09801.733  0.0434       010319.09  0.0434       0
#XS Ineff= 2 , 0
       09941.795                       0
Bank Sta=9801.733,10319.09
Exp/Cntr=0.3,0.1

Type RM Length L Ch R = 1 ,13626.62,71.799400,71.799400,71.799400
XS GIS Cut Line= 2
397691.392232507853195.419954245397417.954732536853775.932107037
#Sta/Elev= 30
9715.37861.602999725.96860.348729737.02257.852289759.12954.703059777.31452.79091
 9847.5645.978579891.77543.388469902.82940.715559913.88336.940669924.93638.23112
 9935.9938.250249980.20536.859899991.25932.0626410002.3132.5086810013.3735.57192
10024.42 35.078510057.5835.8860610090.7434.5329810129.3336.3506210157.0734.47682
10179.17 35.731910201.2835.5763510223.3936.9904410234.44 38.164110246.6640.65922
 10267.641.6297710300.7747.3140710333.9356.7023410344.9861.9782210357.0770.30139
#Mann= 3 , 0 , 0
9715.378  0.0499       09715.378  0.0499       010357.07  0.0499       0
#XS Ineff= 2 , 0
       09930.969        10106.95       0
Bank Sta=9715.378,10357.07
Exp/Cntr=0.3,0.1

Type RM Length L Ch R = 1 ,13554.82,85.523300,85.523300,85.523300
XS GIS Cut Line= 2
397633.883551956853168.293218142397355.020704715853755.315787584
#Sta/Elev= 30
9719.89561.67571 9727.3260.424359760.53352.255829771.60450.080259826.959 44.7787
9893.38541.640819915.52736.137619926.598 37.0468 9948.7437.254129959.81136.55384
9973.64936.503899981.95335.837769993.02430.987389996.95430.5446410004.0930.81397
10015.1733.1972810026.2434.4672710043.5634.4083710059.4535.9386110148.0235.98042
10181.2336.64705 10192.336.2161210214.4437.2178910225.5136.5379710247.66 38.2879
 10269.841.0981610280.8741.7744910336.2256.7335110346.5360.7187510369.7968.21149
#Mann= 3 , 0 , 0
9719.895    0.04       09719.895    0.04       010369.79    0.04       0
#XS Ineff= 2 , 0
       09934.475        10040.53       0
Bank Sta=9719.895,10369.79
Exp/Cntr=0.3,0.1

Type RM Length L Ch R = 1 , 13469.3,91.669500,91.669500,91.669500
XS GIS Cut Line= 4
397569.864454716853130.315787573397476.548482507853342.989398693
 397415.78459364853393.987662599397248.683899165853762.911273676
#Sta/Elev= 30
9729.62463.54233 9756.5859.02805 9778.42 52.97669800.26148.456519822.10145.99726
9833.02245.691469854.86241.592299865.78240.645539909.46440.195159920.38436.61984
9931.30435.012069942.22436.102819980.55235.642389990.00133.374289996.10730.57989
10003.0630.9548910011.6635.1689710016.1136.5614110042.3137.7037210064.2737.33068
10075.2438.1176410108.1838.0668510140.0537.2456610152.0936.0963210217.9636.26055
10272.8537.0644610316.7639.0077310338.7142.6478410404.5848.43484 10446.254.82697
#Mann= 3 , 0 , 0
9729.624    0.04       09729.624    0.04       0 10446.2    0.04       0
#XS Ineff= 2 , 0
       09950.258        10025.81       0
Bank Sta=9729.624,10446.2
Exp/Cntr=0.3,0.1

Type RM Length L Ch R = 1 ,13377.63,33.596900,33.596900,33.596900
XS GIS Cut Line= 2
397497.164801956853064.126551447397167.303690851853741.209884769
#Sta/Elev= 30
9725.63463.522779737.72963.048329759.97660.235379776.24254.818799782.22453.74257
9793.34754.031339804.47151.849859837.841 47.30039890.40540.93067 9926.8338.56587
9937.95435.494499949.07733.419059960.20134.320089982.44834.316639993.57231.26546
10004.5729.8726210015.82 35.077610038.0736.1019410127.0536.68522 10149.3 36.0488
10182.6736.7355110204.92 36.179110305.0337.2888110360.65 38.863210371.77 38.7932
10394.0239.9558110416.2742.0567710438.5242.5610410460.76 43.649410478.79 45.0208
#Mann= 3 , 0 , 0
9725.634    0.04       09725.634    0.04       010478.79    0.04       0
#XS Ineff= 2 , 0
       0                10032.63       0
Bank Sta=9725.634,10478.79
Exp/Cntr=0.3,0.1

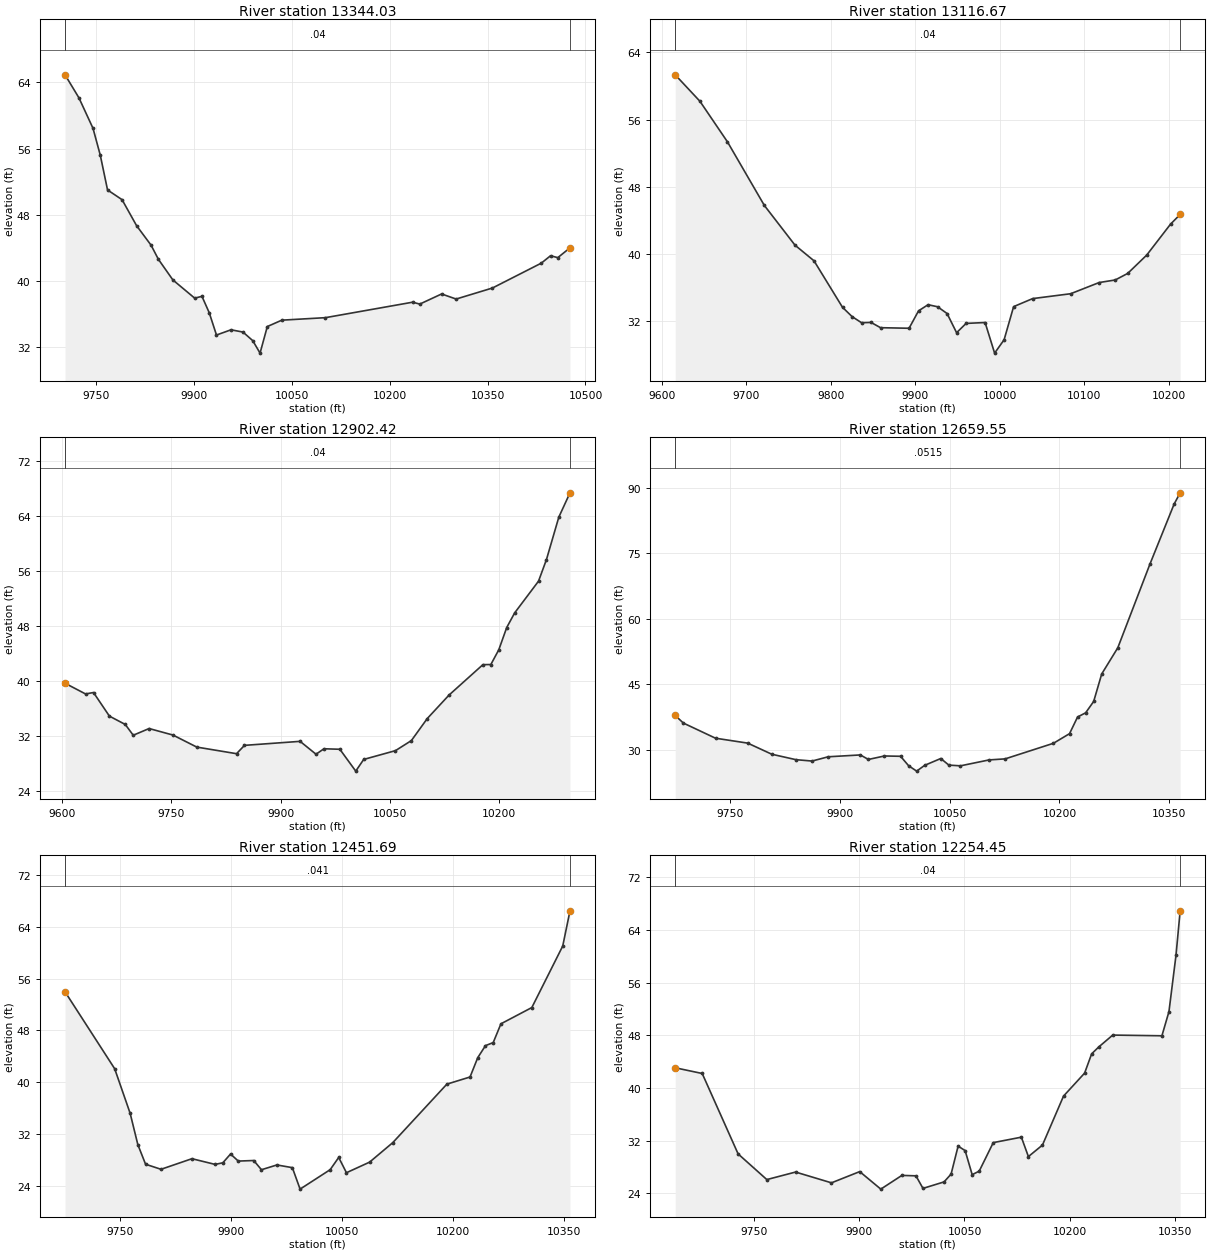
Type RM Length L Ch R = 1 ,13344.03,227.355100,227.355100,227.355100
XS GIS Cut Line= 2
397474.313239454853036.471748238397135.771572771853731.784248221
#Sta/Elev= 30
9702.96664.914739724.24162.132229745.81958.440139756.94155.196449768.06350.99001
9790.30849.812269812.55346.666619834.79744.30086 9845.9242.603599868.16440.10242
9901.53137.902539912.65438.121289923.77636.143279934.89833.441369957.143 34.0738
 9975.5233.79926 9990.5132.7555410001.63 31.252110012.7534.46717   1003535.23917
10101.7335.54139 10235.237.4111610246.32 37.185310279.6938.4078610301.9437.79417
10357.5539.1282410432.3942.1362310446.53 43.030110457.6542.8031810476.3243.98795
#Mann= 3 , 0 , 0
9702.966    0.04       09702.966    0.04       010476.32    0.04       0
#XS Ineff= 2 , 0
       0                10020.23       0
Bank Sta=9702.966,10476.32
Exp/Cntr=0.3,0.1

Type RM Length L Ch R = 1 ,13116.67,214.259700,214.259700,214.259700
XS GIS Cut Line= 2
397323.271572797852848.971748209397049.834072769853380.221748224
#Sta/Elev= 30
 9615.9961.340249645.26458.190219677.76753.371479721.46945.795149757.73341.07066
9780.226 39.20779813.96733.672229825.21432.574619836.46131.840599847.70831.87595
9858.95531.249919892.69531.183049903.94233.258299915.18933.985029926.43633.74104
9937.68332.93603 9948.93 30.65269960.17631.75924 9982.6731.865069993.91728.22335
10005.1629.8149310016.4133.75616 10038.934.7114210083.89  35.29110117.6336.62375
10136.6436.9285810151.3737.7064110173.8739.8873410202.1943.5847610213.48 44.7236
#Mann= 3 , 0 , 0
 9615.99    0.04       0 9615.99    0.04       010213.48    0.04       0
#XS Ineff= 2 , 0
       09925.744                       0
Bank Sta=9615.99,10213.48
Exp/Cntr=0.3,0.1

Type RM Length L Ch R = 1 ,12902.42,242.869300,242.869300,242.869300
XS GIS Cut Line= 2
397114.938239457852729.180081539396838.896572768853364.596748237
#Sta/Elev= 30
9604.19939.64754 9632.35  38.0919643.25338.297669665.05934.869029686.86433.65409
9697.76732.089569719.573 33.06359752.28232.11618 9784.9930.366019839.50529.40778
9850.40830.618859926.728 31.20179948.53329.329689959.43630.122969981.24230.05105
10003.0526.8734110013.9528.5721410057.56  29.85210079.3731.3123610101.1734.51712
10131.0837.9339410177.4942.34655 10188.442.36676 10199.344.50817 10210.247.74838
10221.1149.8767610253.8154.4815610264.7257.6274610281.6763.7917710296.9967.32193
#Mann= 3 , 0 , 0
9604.199    0.04       09604.199    0.04       010296.99    0.04       0
#XS Ineff= 2 , 0
       09924.594                       0
Bank Sta=9604.199,10296.99
Exp/Cntr=0.3,0.1

Type RM Length L Ch R = 1 ,12659.55,207.853200,207.853200,207.853200
XS GIS Cut Line= 2
396875.354906142852684.909248204396591.500739486853312.513414889
#Sta/Elev= 30
 9675.8437.894849686.91536.155249730.81632.686989774.71731.563139807.64329.01848
9840.56927.773459862.51927.46188 9884.4728.436139928.37128.860139939.34627.82782
9961.29628.621539983.24728.551379994.22226.39022 10005.225.1554110016.1726.48601
10038.1228.04387 10049.126.5339310064.9626.3679210103.9727.7185210125.9227.95881
10191.78 31.526610213.7333.72705 10224.737.5419610235.6838.4933710246.6541.09251
10257.6347.3872210279.5853.3784110323.48 72.549710356.4186.2589310364.6588.82694
#Mann= 3 , 0 , 0
 9675.84  0.0515       0 9675.84  0.0515       010364.65  0.0515       0
#XS Ineff= 2 , 0
       09811.023                       0
Bank Sta=9675.84,10364.65
Exp/Cntr=0.3,0.1

Type RM Length L Ch R = 1 ,12451.69,197.245000,197.245000,197.245000
XS GIS Cut Line= 2
396646.188239486852580.742581558396453.479906113 853234.38841488
#Sta/Elev= 30
9676.07853.98118 9743.0742.077669763.92135.191239774.34730.326469784.77227.29925
9805.62426.517719847.326 28.15639878.60227.275319889.028 27.52279899.453 28.8817
9909.879 27.7888 9930.7327.876499941.15626.449189962.00727.189079982.85826.77217
9993.28323.44857 10033.926.4600710045.4128.3516510055.84  25.98610087.1127.62576
10118.3930.6438210191.3739.6932410222.6540.8002610233.0743.79411 10243.545.65519
10253.9246.1253310264.35 49.031210306.0551.5486210347.7561.0675710357.5466.51416
#Mann= 3 , 0 , 0
9676.078   0.041       09676.078   0.041       010357.54   0.041       0
#XS Ineff= 2 , 0
       09803.596                       0
Bank Sta=9676.078,10357.54
Exp/Cntr=0.3,0.1

Type RM Length L Ch R = 1 ,12254.45,284.041800,284.041800,284.041800
XS GIS Cut Line= 3
396419.625739484852497.409248236396370.146572768852723.971748214
396341.500739456853210.950914869
#Sta/Elev= 30
9637.69743.062789676.17442.194739727.35229.971429768.29526.071019809.23827.21683
9860.41725.577349900.68227.284899930.73324.620979960.78526.70752 9980.8226.64184
9990.83724.7329510020.89 25.719310030.9126.9060210040.9231.1569210050.9430.47291
10060.9626.8209310070.98 27.353310091.0131.6886410131.0832.51727 10141.129.56546
10161.1331.3147310191.1838.7625710221.2342.2544910231.2545.1792610241.2746.21888
 10261.3 48.032410331.42 47.926710341.44 51.601610351.4660.1490210357.4266.91683
#Mann= 3 , 0 , 0
9637.697    0.04       09637.697    0.04       010357.42    0.04       0
#XS Ineff= 2 , 0
       09904.381                       0
Bank Sta=9637.697,10357.42
Exp/Cntr=0.3,0.1

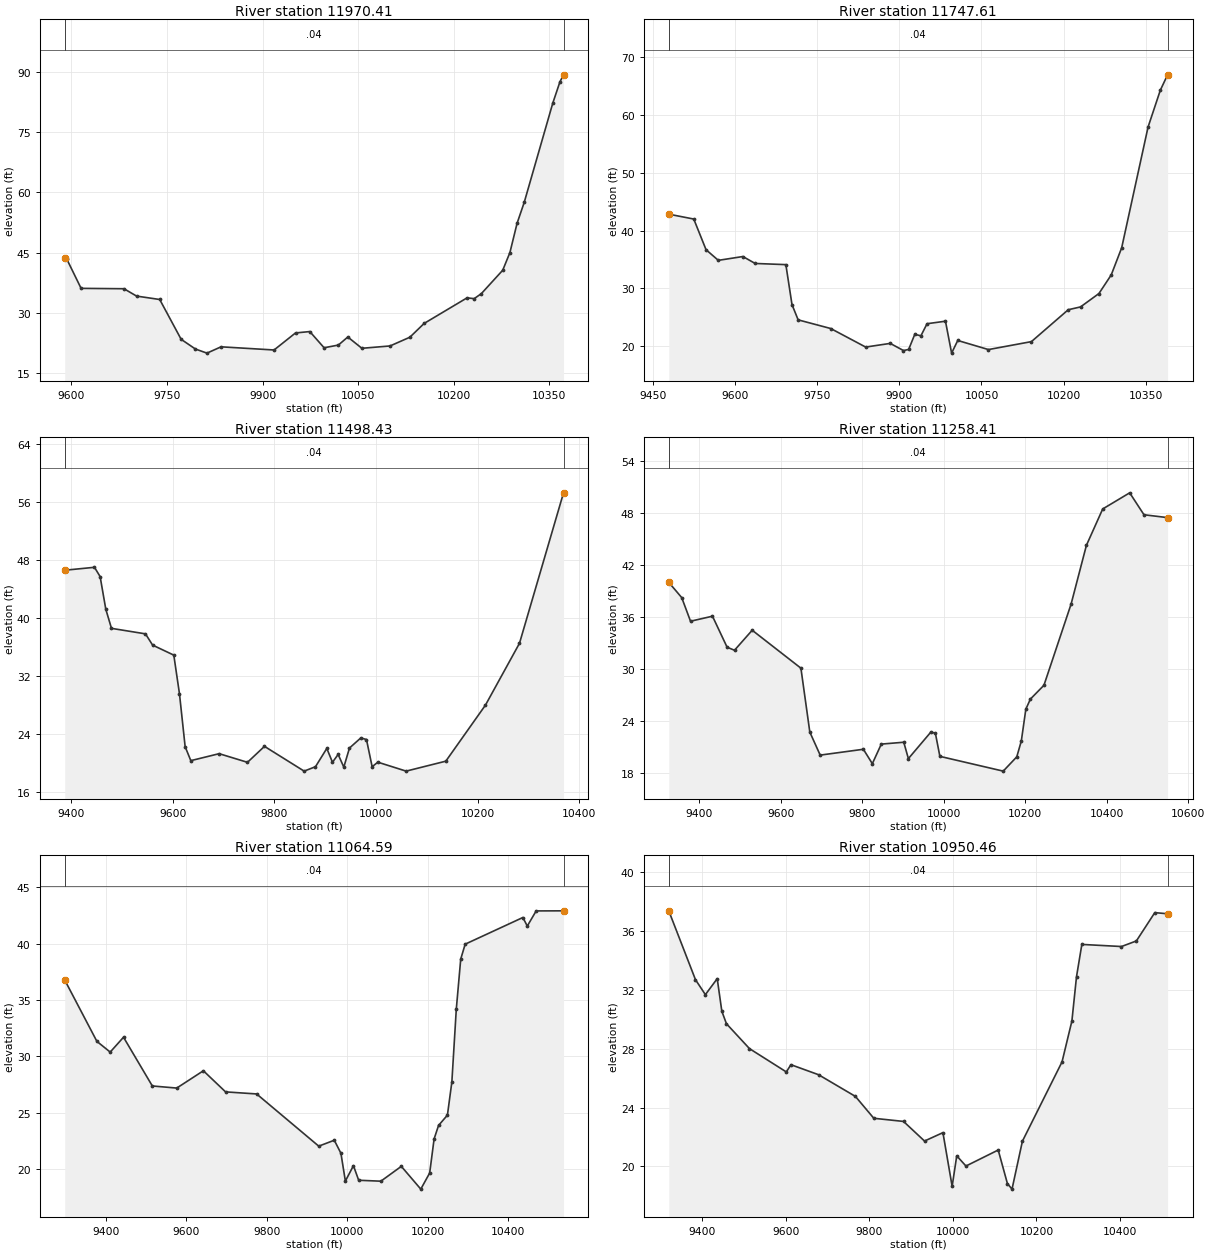
Type RM Length L Ch R = 1 ,11970.41,222.796000,222.796000,222.796000
XS GIS Cut Line= 2
395904.000739453852552.096748221396258.167406113853250.013414855
#Sta/Elev= 30
9589.55143.528079592.80643.351569615.234   36.059682.518  35.9569702.24934.12103
9738.58733.267859772.22923.317169794.657  20.8879812.739 19.86899834.83721.44484
 9918.0120.653729951.652 24.90999974.07925.256159996.50721.2096510018.9421.88552
10033.7223.8966410055.8221.0765910100.0121.6617410131.07 23.8397 10153.527.29124
10220.7933.67667   1023233.4802210243.2134.72573 10276.840.5807210288.0744.98863
10299.2852.28728 10310.557.5236510355.3582.3321210366.5787.6521110372.1989.39706
#Mann= 3 , 0 , 0
9589.551    0.04       09589.551    0.04       010372.19    0.04       0
#XS Ineff= 2 , 0
       0                               0
Bank Sta=9589.551,10372.19
Exp/Cntr=0.3,0.1

Type RM Length L Ch R = 1 ,11747.61,249.178700,249.178700,249.178700
XS GIS Cut Line= 2
395651.396572768852544.284248234396062.854906111853356.784248237
#Sta/Elev= 30
9479.03742.844659524.67642.002129547.09536.702379569.51334.862419614.34935.52308
9636.76834.325419692.814 34.12249704.02327.217899715.23224.577049774.76223.07943
9838.53319.873779883.36920.507659907.569 19.27539916.99719.459449928.20622.06862
9939.41521.824259950.62423.909039984.25224.345329995.46118.8265510006.6721.01302
10062.72 19.442410141.1820.8150910208.4326.3271510230.8526.8139910264.4829.12803
 10286.932.3419110305.9937.0297610354.1557.8969610376.5764.2738710389.7866.92968
#Mann= 3 , 0 , 0
9479.037    0.04       09479.037    0.04       010389.78    0.04       0
#XS Ineff= 2 , 0
       0                               0
Bank Sta=9479.037,10389.78
Exp/Cntr=0.3,0.1

Type RM Length L Ch R = 1 ,11498.43,240.020900,240.020900,240.020900
XS GIS Cut Line= 2
395388.375739483852562.513414896395823.271572768853442.721748233
#Sta/Elev= 30
9387.13646.604199445.67947.009249456.83345.721399467.98741.206459479.14138.56733
9546.06537.805399560.11636.250959601.83534.864329612.98929.516829624.14322.20647
9635.297 20.27119691.06721.236869746.83720.040879780.29922.249869858.37718.82326
9880.68519.433689902.99321.963249914.14720.047799925.301 21.13539936.45519.37548
9947.60922.016879969.91723.414919981.07123.192189992.22519.4300910003.3820.06096
10059.1518.8234510137.2320.2000410215.3127.9566410282.2336.5011310368.9257.30856
#Mann= 3 , 0 , 0
9387.136    0.04       09387.136    0.04       010368.92    0.04       0
#XS Ineff= 2 , 0
       0                               0
Bank Sta=9387.136,10368.92
Exp/Cntr=0.3,0.1

Type RM Length L Ch R = 1 ,11258.41,193.824300,193.824300,193.824300
XS GIS Cut Line= 6
395171.309187648852595.489772688395222.230364085 852721.69791194
395339.622329889852994.091075925395392.404705404853108.810769887
395601.020863892853541.272409736395679.507169368853709.265212345
#Sta/Elev= 30
9324.73940.012829356.56138.252899378.128 35.53419432.04436.113899467.95332.53725
9486.12732.191039529.54834.49604 9649.15  30.126 9671.0122.76221 9696.45 20.1098
9802.48620.783559824.50119.123219846.51721.379249901.67321.593489912.97819.70622
9968.15522.762359979.23622.641859990.31619.9664710145.8318.2651210179.1619.91473
10190.2721.7415610201.3825.4069110212.49 26.562510245.8228.1570110312.4837.51069
10350.0744.2777710390.0848.46792 10456.350.3263310491.4147.7995810549.3147.47111
#Mann= 3 , 0 , 0
9324.739    0.04       09324.739    0.04       010549.31    0.04       0
#XS Ineff= 2 , 0
       0                               0
Bank Sta=9324.739,10549.31
Exp/Cntr=0.3,0.1

Type RM Length L Ch R = 1 ,11064.59,114.122800,114.122800,114.122800
XS GIS Cut Line= 2
394973.537136496852662.528281674395494.370469838853786.660226131
#Sta/Elev= 30
9298.24536.782369378.11731.336799411.18130.383869444.24431.702299515.81127.37722
9576.49927.190179642.626 28.72599697.73226.85169 9774.8826.668679929.17722.03553
9967.77222.559459984.28321.402929995.30418.9362410015.3520.3035510028.3719.00768
10083.4718.9249910134.2820.2425310182.6618.2204810204.7119.6516510215.7322.67916
10226.7523.8711210248.7924.7890810259.8127.7315710270.8334.1913710281.8538.64062
10292.8839.9628310436.1542.3292310447.1741.5713810469.2142.9147710537.1742.92246
#Mann= 3 , 0 , 0
9298.245    0.04       09298.245    0.04       010537.17    0.04       0
#XS Ineff= 2 , 0
       09795.636                       0
Bank Sta=9298.245,10537.17
Exp/Cntr=0.3,0.1

Type RM Length L Ch R = 1 ,10950.46,341.472900,341.472900,341.472900
XS GIS Cut Line= 2
394878.051025396852729.802587266395381.523247599853812.701892829
#Sta/Elev= 30
9319.67837.36334  9383.632.68609 9407.3231.66919 9435.6932.755819446.71830.53882
9457.74629.693599512.88528.001629601.109 26.41779612.13726.909439678.30526.22852
9766.52924.755069810.55423.269369881.71323.055419931.94821.72281 9976.0622.29275
9998.11618.6460510009.1420.71781 10031.220.02483 10108.421.1124110130.4518.83382
10141.4818.4556610166.3521.7113210261.2327.1014810284.8429.8782310295.8732.88535
10308.6735.0812710403.5434.9381510439.2335.3172410483.3537.24138 10513.937.16276
#Mann= 3 , 0 , 0
9319.678    0.04       09319.678    0.04       0 10513.9    0.04       0
#XS Ineff= 2 , 0
       09826.375                       0
Bank Sta=9319.678,10513.9
Exp/Cntr=0.3,0.1

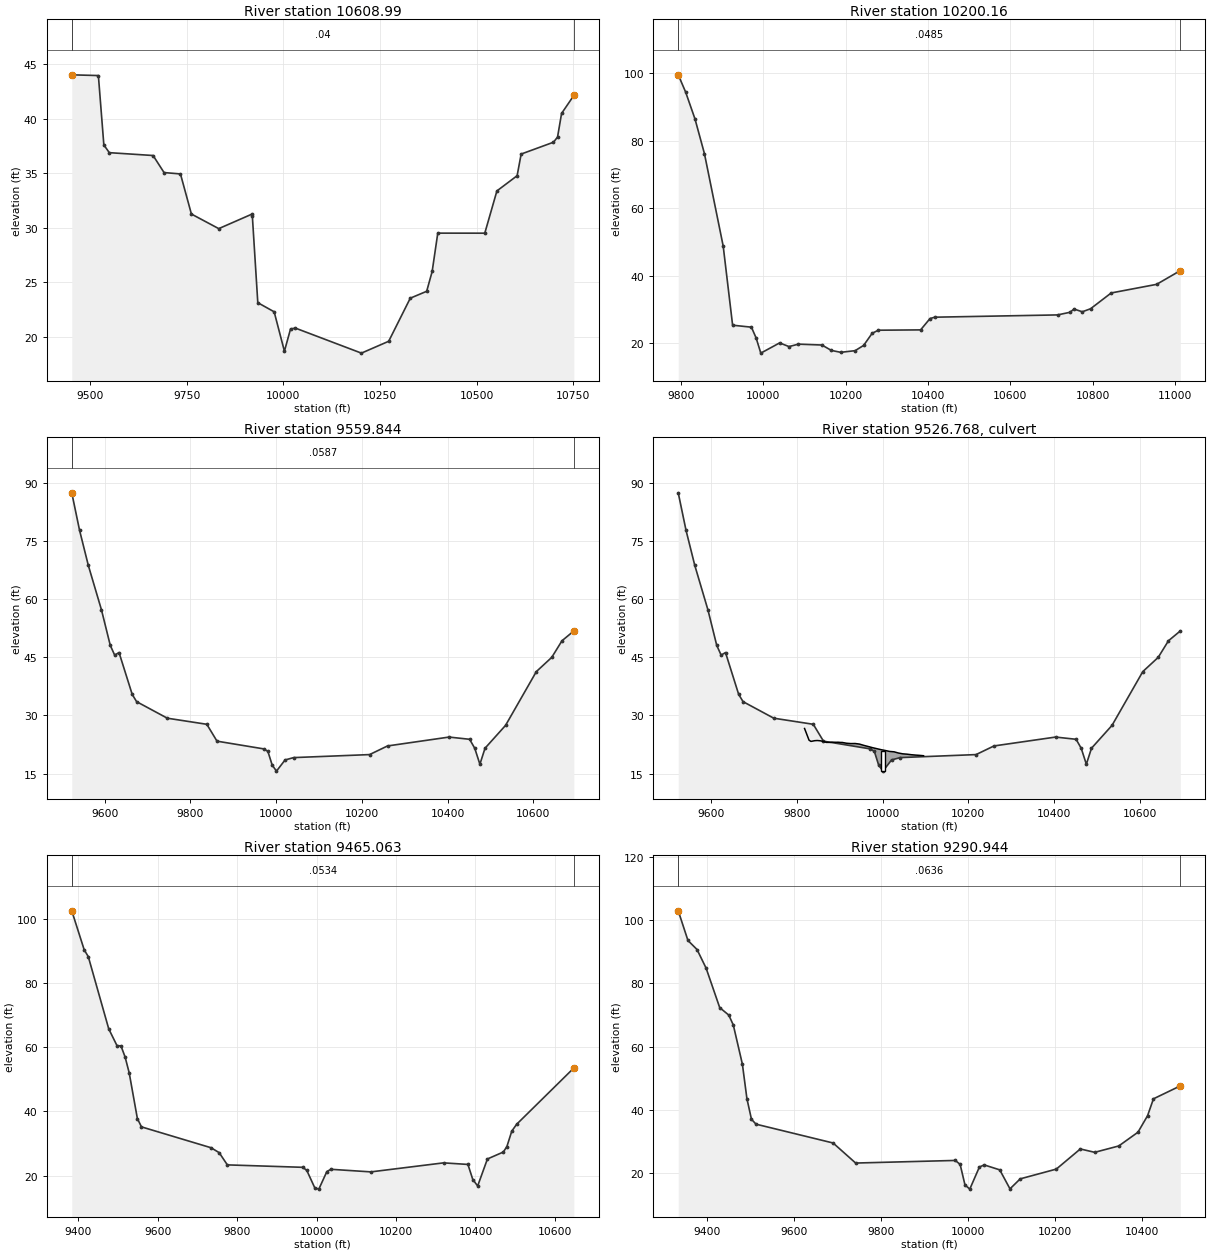
Type RM Length L Ch R = 1 ,10608.99,408.832800,408.832800,408.832800
XS GIS Cut Line= 3
394463.896572769853096.367581524395153.068106131853783.272136856
395465.340676537853879.460382191
#Sta/Elev= 30
9452.05244.038519520.94243.971749535.10837.599739549.27336.893599662.59736.63201
9690.92835.067119733.42534.941689761.75631.260129832.58329.920419917.57631.23862
9919.53431.080969933.65223.122259976.00922.2857810002.5718.6683710018.3720.70539
 10030.920.7913610201.9118.4925910272.5119.5805810328.3823.5362110370.8724.16872
10385.0425.9869110399.5829.5068410521.2829.5030610552.6733.3811110604.9934.77771
10615.4536.7658810699.1637.8522210709.6338.3253410720.0940.4936910751.8442.14704
#Mann= 3 , 0 , 0
9452.052    0.04       09452.052    0.04       010751.84    0.04       0
#XS Ineff= 2 , 0
       0                               0
Bank Sta=9452.052,10751.84
Exp/Cntr=0.3,0.1

Type RM Length L Ch R = 1 ,10200.16,640.313200,640.313200,640.313200
XS GIS Cut Line= 3
394349.313239485853617.200914925394948.271572793853947.930081574
395482.360940247853902.326578936
#Sta/Elev= 30
9792.91599.463619810.834 94.3765 9833.6886.379489856.52776.164579902.21948.74339
9925.06625.345139970.75924.760459982.182 21.57789993.60517.07733 10039.320.10035
10062.1419.0181510084.9919.7354210142.1119.4777910164.95 17.8845 10187.817.31577
 10222.817.8026910243.4919.3623610264.1822.9417810279.1923.8608410381.9923.95884
10404.8427.3111310416.2627.7147110714.7128.3880910744.8229.1603810754.8530.12294
10774.9329.32033   1079530.2097310845.1834.8890910955.58 37.438311013.1541.50097
#Mann= 3 , 0 , 0
9792.915  0.0485       09792.915  0.0485       011013.15  0.0485       0
#XS Ineff= 2 , 0
       0                               0
Bank Sta=9792.915,11013.15
Exp/Cntr=0.3,0.1

Type RM Length L Ch R = 1 ,9559.844,94.781300,94.781300,94.781300
XS GIS Cut Line= 6
394197.577128335853947.279039912394135.827942213854267.954198775
394186.226805264854299.690808725394383.705844832854283.519915237
394464.508870961854298.671090974394751.526545377854708.057192982
#Sta/Elev= 30
9522.97587.380529541.125 77.73589561.60968.669689592.33457.195029612.81848.06932
 9623.0645.556239633.30246.210159664.02835.42751 9674.2733.556039745.96329.29227
9838.13127.722259861.91523.372799970.52421.389599980.56920.760799990.61417.22898
10000.6615.6501910020.7518.5296710040.8419.1360310217.9919.91212 10259.822.13909
10403.5424.4291810451.4523.8552910463.4221.53626 10475.417.4226610487.3821.55119
10535.2927.4426910607.1641.3053810643.0944.9732710667.0549.2566810694.6651.78224
#Mann= 3 , 0 , 0
9522.975  0.0587       09522.975  0.0587       010694.66  0.0587       0
#XS Ineff= 2 , 0
       0                               0
Bank Sta=9522.975,10694.66
Exp/Cntr=0.3,0.1

Type RM Length L Ch R = 2 ,9526.768,,,
Bridge Culvert--1,0,-1,-1, 0
Deck Dist Width WeirC Skew NumUp NumDn MinLoCord MaxHiCord MaxSubmerge Is_Ogee
19.176,56.43,2.6,0,36,36, , , 0.95, 0, 0,0,,
 9817.77 9828.23 9832.70 9841.70 9847.62 9855.17 9862.55 9868.64 9877.48 9882.10
 9892.41 9895.57 9901.84 9905.56 9915.65 9925.74 9935.83 9936.45 9945.92 9956.02
 9966.11 9976.20 9986.29 9996.3810006.4710010.7910016.5710026.6610036.7510046.84
10056.9310067.0210077.1210085.1410087.2110095.44
   26.64   23.63   23.31   23.50   23.54   23.46   23.28   23.06   23.06   23.11
   23.08   23.10   23.04   23.04   22.84   22.75   22.77   22.76   22.62   22.29
   22.00   21.70   21.44   21.18   20.96   20.86   20.72   20.63   20.32   20.11
   20.02   19.88   19.78   19.72   19.70   19.62
                                                                                
                                                                                
                                                                                
                                                
 9817.77 9828.23 9832.70 9841.70 9847.62 9855.17 9862.55 9868.64 9877.48 9882.10
 9892.41 9895.57 9901.84 9905.56 9915.65 9925.74 9935.83 9936.45 9945.92 9956.02
 9966.11 9976.20 9986.29 9996.3810006.4710010.7910016.5710026.6610036.7510046.84
10056.9310067.0210077.1210085.1410087.2110095.44
   26.64   23.63   23.31   23.50   23.54   23.46   23.28   23.06   23.06   23.11
   23.08   23.10   23.04   23.04   22.84   22.75   22.77   22.76   22.62   22.29
   22.00   21.70   21.44   21.18   20.96   20.86   20.72   20.63   20.32   20.11
   20.02   19.88   19.78   19.72   19.70   19.62
                                                                                
                                                                                
                                                                                
                                                
BR Coef=-1 , 0 , 0 ,, 0 ,,,0.8,-1,,0,
WSPro=,,,, 1 ,,,, 0 ,,,, 0 ,,,,-1 ,-1 ,-1 , 0 , 0 , 0 , 0 , 0
Culvert=2,5,10,56.43,0.013,0.4,1,8,2,15.744,10000,15.365,10000,Culvert #1, 0, 19.176
Culvert Bottom n=0.013
BC Design=,, 0 ,, 0 ,,,,,,

Type RM Length L Ch R = 1 ,9465.063,174.119200,174.119200,174.119200
XS GIS Cut Line= 6
394185.532857532853924.601088578394092.216885277854303.290324667
394106.992805366 854380.58404388394371.740249815854367.033037333
394452.564549635854383.081629871394707.855666527854742.428769238
#Sta/Elev= 30
9383.378102.43129414.68690.287199424.98688.163269476.48165.67244 9497.0860.49626
9507.37960.343189517.67856.917149527.97751.990679548.57537.755249558.87435.16476
 9733.9628.671829754.55827.138629775.13623.329559965.12322.571689975.21821.60136
 9995.4116.1555810005.51 15.7807 10025.721.2453110035.7921.9540810136.6521.15014
10319.6223.9569410380.9523.4696610393.22 18.773110405.4816.7608610430.0225.16799
10470.0727.3311210479.0829.0392610491.3533.8286210503.6235.9729710647.66  53.498
#Mann= 3 , 0 , 0
9383.378  0.0534       09383.378  0.0534       010647.66  0.0534       0
#XS Ineff= 2 , 0
       09684.961                       0
Bank Sta=9383.378,10647.66
Exp/Cntr=0.3,0.1

Type RM Length L Ch R = 1 ,9290.944,153.818000,153.818000,153.818000
XS GIS Cut Line= 5
 394176.47204848 853923.56621153 394064.66649298854302.038433723
394104.597048496854506.899544831394207.027604055854555.510655958
394603.124165586854741.214273766
#Sta/Elev= 30
9333.386102.89679355.73693.52926 9376.5990.677149397.44584.797539428.726 72.3323
9449.58169.967219460.00866.822589480.862 54.4708 9491.2943.555939501.71737.08107
9512.14435.519759689.40729.571219741.23323.240049970.39724.064559981.46622.80039
9992.53516.34677 10003.6 15.003210025.7421.9931610036.81  22.64710072.4821.08835
10096.0415.0904310119.59 18.250310202.5121.3270110257.7327.6873110290.8626.62784
10346.0928.6352910390.2632.9770110412.3538.2025710425.8443.5236210487.5947.60999
#Mann= 3 , 0 , 0
9333.386  0.0636       09333.386  0.0636       010487.59  0.0636       0
#XS Ineff= 2 , 0
       09658.331                       0
Bank Sta=9333.386,10487.59
Exp/Cntr=0.3,0.1

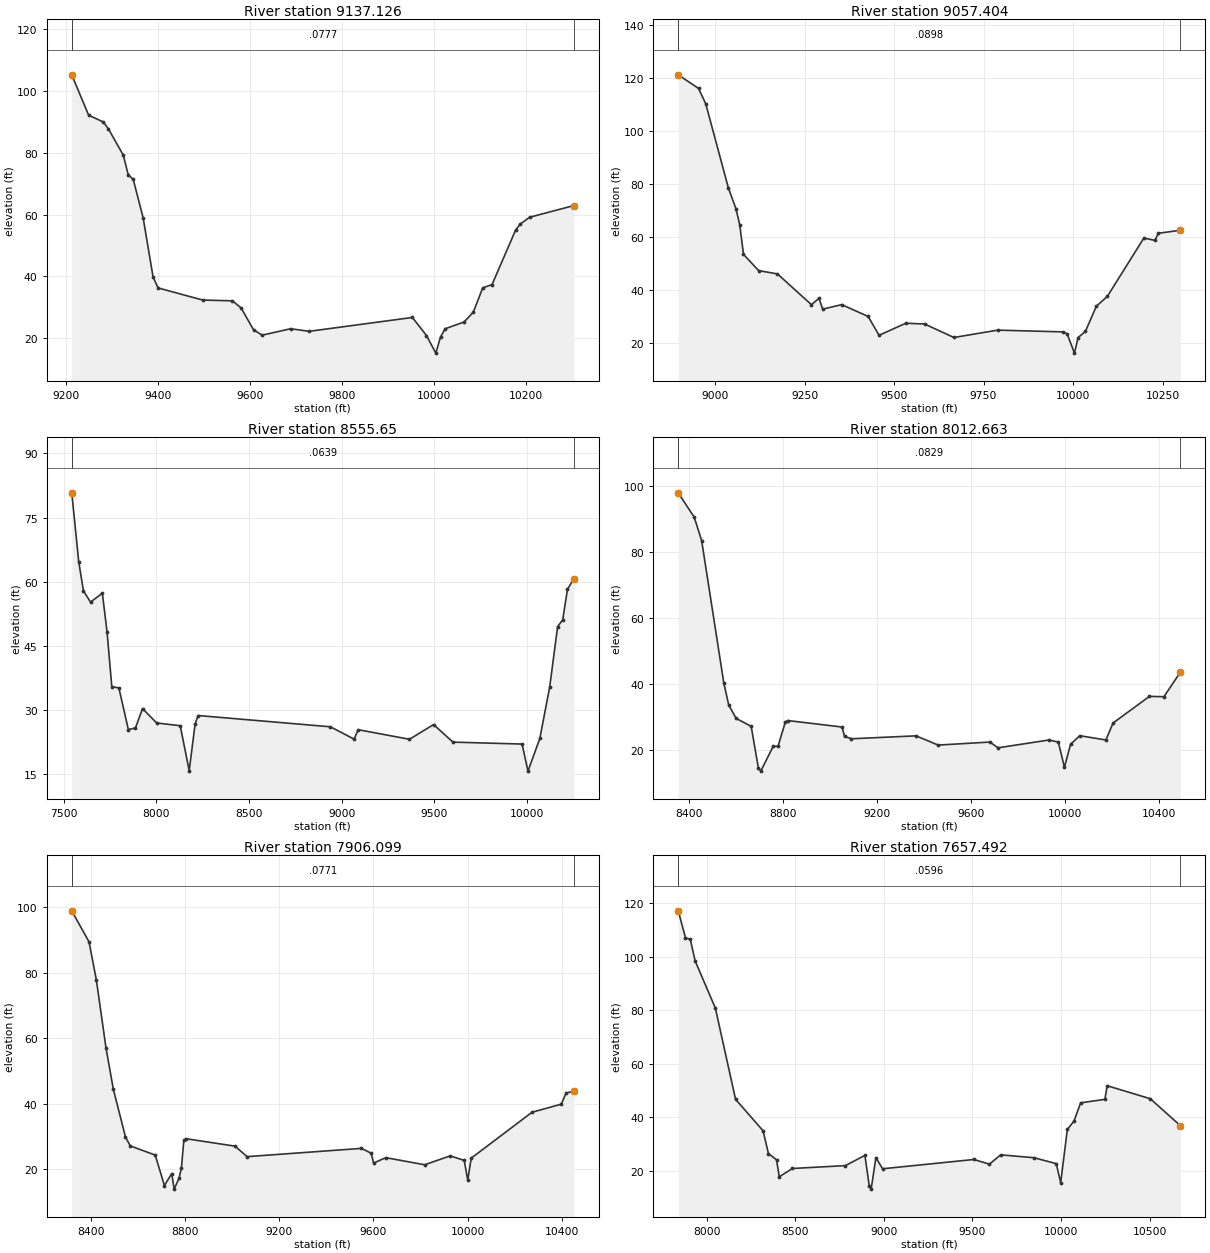
Type RM Length L Ch R = 1 ,9137.126,79.721600,79.721600,79.721600
XS GIS Cut Line= 3
   394171.553067853911.124081878394015.303066997854301.749081874
394140.089968971854959.409781342
#Sta/Elev= 30
9213.493105.28889249.97892.236339282.28989.97614 9293.0687.759779325.37179.25403
9336.141 72.84669346.911 71.42069368.45258.933089389.99339.806919400.76336.22254
9497.69632.291199562.31832.037579581.17329.729649608.09922.64519 9626.94 20.9058
 9688.4122.985639729.123 22.15899953.04926.648159983.58420.7967710003.9415.08643
10014.1220.30885 10024.322.9953710065.01 25.157910085.3728.3617210105.73 36.2382
10126.0837.3170810176.9754.9131310187.1556.9139410207.5159.11755 10303.662.91643
#Mann= 3 , 0 , 0
9213.493  0.0777       09213.493  0.0777       0 10303.6  0.0777       0
#XS Ineff= 2 , 0
       09599.747                       0
Bank Sta=9213.493,10303.6
Exp/Cntr=0.3,0.1

Type RM Length L Ch R = 1 ,9057.404,501.753900,501.753900,501.753900
XS GIS Cut Line= 3
394142.966713225853632.175276553393926.761400344854278.311581887
394069.433315979854984.795405149
#Sta/Elev= 30
8897.387121.30048954.008116.16348974.181110.35739037.45178.530599058.54170.68538
9069.08664.636259079.63153.444219121.81147.308839174.53546.03354 9269.4434.41016
 9290.53 36.83849300.66232.71931  9353.834.431829427.61529.975019458.23222.84501
9533.06527.40313 9585.5627.102929667.17522.010259789.59824.795729973.23124.12747
9983.43323.3956310003.8416.1018910014.04 21.994410034.4424.3018110065.0533.83313
10095.65 37.530310197.6759.5961510228.2858.7403910238.4861.4120510299.4862.54653
#Mann= 3 , 0 , 0
8897.387  0.0898       08897.387  0.0898       010299.48  0.0898       0
#XS Ineff= 2 , 0
       09627.414                       0
Bank Sta=8897.387,10299.48
Exp/Cntr=0.3,0.1

Type RM Length L Ch R = 1 , 8555.65,542.987200,542.987200,542.987200
XS GIS Cut Line= 3
392362.334072768852765.638414863 393127.95907277853734.388414884
393635.771572767855117.200914863
#Sta/Elev= 30
7544.00380.762627581.42764.706097606.91957.873667645.15755.245567708.88757.31599
 7734.3848.268427759.87235.50595 7798.1135.193287849.09425.481767887.33225.83796
 7925.5730.376058002.04627.005358128.89726.370788177.27915.890578209.53526.86037
8225.662 28.7495 8939.2226.116539067.05523.227569088.36125.443079365.33923.20365
9495.41126.638799599.70422.538939972.55822.0881910004.5215.7637410068.4423.38669
 10121.735.4309110164.3149.5031910191.6251.0889410217.5858.2031510251.8860.73033
#Mann= 3 , 0 , 0
7544.003  0.0639       07544.003  0.0639       010251.88  0.0639       0
#XS Ineff= 2 , 0
       09478.339                       0
Bank Sta=7544.003,10251.88
Exp/Cntr=0.3,0.1

Type RM Length L Ch R = 1 ,8012.663,106.563700,106.563700,106.563700
XS GIS Cut Line= 4
392500.446858734853429.997899771392963.988525391854881.386788651
393172.321858764855131.386788636393243.502414286855412.636788636
#Sta/Elev= 30
8353.18397.927888421.41990.547948452.91283.483788547.39140.383638568.38633.72778
8599.87929.681588663.96927.291838694.35814.820418704.85513.738778757.34321.18972
8778.33921.273778809.83228.658588820.32929.037059051.27727.075119061.77524.21738
9091.26623.527689366.20624.411659460.68521.618459681.135 22.53469715.77720.79533
9933.56923.16503 9972.6222.504449998.65414.8938710024.6921.8621810063.7424.45917
10175.1723.1656210205.9528.2993710360.6836.3427410422.5736.2565810492.3443.65056
#Mann= 3 , 0 , 0
8353.183  0.0829       08353.183  0.0829       010492.34  0.0829       0
#XS Ineff= 2 , 0
       09042.556                       0
Bank Sta=8353.183,10492.34
Exp/Cntr=0.3,0.1

Type RM Length L Ch R = 1 ,7906.099,248.607600,248.607600,248.607600
XS GIS Cut Line= 4
392486.905192077853434.164566442392875.446858764 854947.35901086
393083.780192047855176.525677547393151.488525391855426.525677547
#Sta/Elev= 30
8319.76698.867338392.89989.419528423.87277.90945 8465.1757.010798496.14344.46343
8547.76529.864058568.41427.148078673.98524.368268712.95515.057078743.928 18.7289
8754.25313.977988774.90217.271958785.22620.50509 8795.5528.972218805.87529.34182
9012.36327.091419063.98523.885319549.23126.404729590.52824.936899600.85321.92152
9652.475 23.57599817.665 21.41099925.98124.121099985.44522.7386410000.4916.74043
10015.1823.4167510273.0637.4226310397.3839.89095 10418.143.3115510450.7643.82518
#Mann= 3 , 0 , 0
8319.766  0.0771       08319.766  0.0771       010450.76  0.0771       0
#XS Ineff= 2 , 0
       09011.742        10209.68       0
Bank Sta=8319.766,10450.76
Exp/Cntr=0.3,0.1

Type RM Length L Ch R = 1 ,7657.492,492.835100,492.835100,492.835100
XS GIS Cut Line= 6
391364.727844123853451.722665454391600.277210649853676.242332921
391813.037371672  853916.0054412392171.029420362854402.575436084
392768.739354316855185.035128366393124.892061629855668.142895567
#Sta/Elev= 30
7838.831117.09137879.834107.02227906.924106.44657934.06598.415248048.57280.73888
8162.51746.704068317.93234.934368348.25726.411488393.74624.125658409.35517.76349
8483.65820.86046 8782.7921.929038892.96925.754328917.45314.348988928.07313.14657
8955.11724.918488992.48720.746759507.99524.216399596.19922.469719659.20225.95239
9847.86724.875959973.33622.66645 9998.4315.5288910036.0735.4344610073.7138.57651
10111.1245.3789410248.2646.6731910260.7351.7704310504.5246.9065210673.9636.86836
#Mann= 3 , 0 , 0
7838.831  0.0596       07838.831  0.0596       010673.96  0.0596       0
#XS Ineff= 2 , 0
       08960.934        10156.81       0
Bank Sta=7838.831,10673.96
Exp/Cntr=0.3,0.1