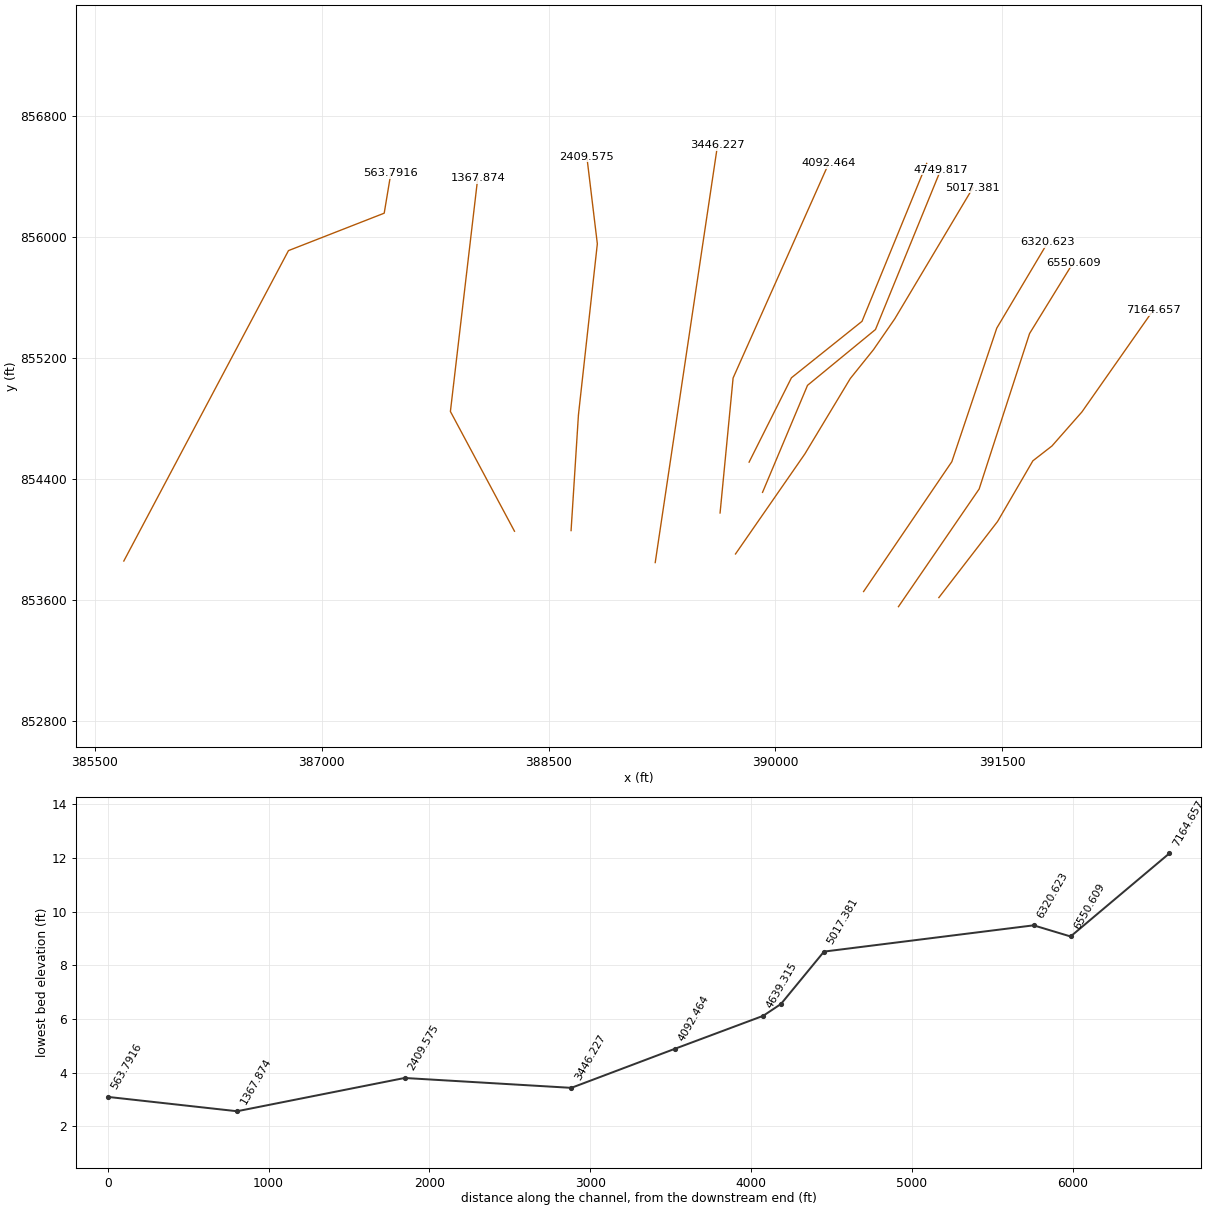
HEC-RAS study 6977_ras.prj: 6977

--- 6977_ras.g01 (geometry) --- (continued)

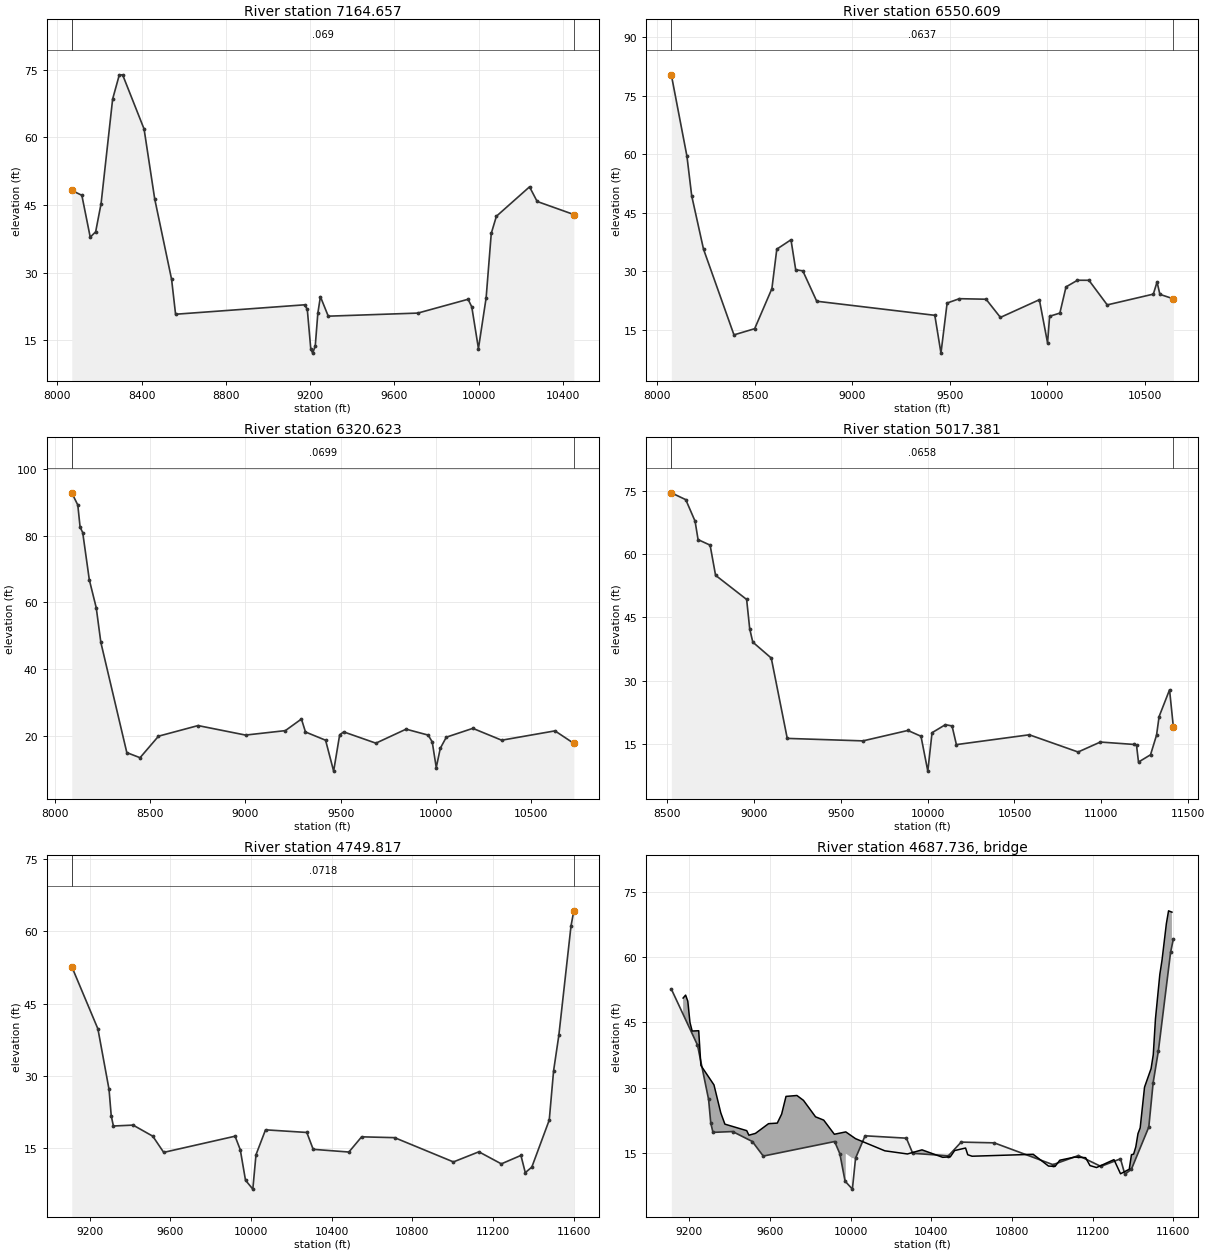
Type RM Length L Ch R = 1 ,7164.657,614.047600,614.047600,614.047600
XS GIS Cut Line= 6
391080.348082409853618.921044725391468.736552259854122.390401623
391701.800051003854522.975677793391827.990126687854621.133837726
392026.323151198  854846.5211326392497.785995496855519.181268968
#Sta/Elev= 30
8068.29948.233458116.12747.153898155.89137.877198181.67239.061178207.45345.32165
8262.31368.495038294.007 73.86178309.85573.842638411.56461.84193 8461.8646.37989
8542.18128.506478560.98920.790099173.38222.879539186.19421.86776 9202.9713.00351
9211.90212.169889224.04913.786499236.25221.025639248.45524.684729285.70620.36185
9710.80121.045029949.33524.10827 9966.8822.421899998.50813.1840310035.0224.41624
10059.3638.71099 10083.742.5085310241.0249.0314910277.2245.7887910451.1942.89251
#Mann= 3 , 0 , 0
8068.299   0.069       08068.299   0.069       010451.19   0.069       0
#XS Ineff= 2 , 0
       09071.295        10195.01       0
Bank Sta=8068.299,10451.19
Exp/Cntr=0.3,0.1

Type RM Length L Ch R = 1 ,6550.609,229.986500,229.986500,229.986500
XS GIS Cut Line= 4
390813.299445797853558.883497585391346.632779157854336.661275344
391679.966112504855364.439053142391968.855001357855833.883497569
#Sta/Elev= 30
8071.619 80.30488151.786  59.4428176.03649.355068236.66235.689848392.91213.74406
8499.00715.32656 8587.4225.586478612.54435.686228685.29538.086088709.54530.40003
8745.92130.137628817.29422.357239422.94218.75038 9454.489.0746839486.01821.89415
9549.09523.008579685.76122.869399759.35118.216899959.09422.7451510001.1411.69846
10011.6618.5059410064.2219.3208610095.8326.0272810154.5427.7301910213.2527.71904
10307.1821.4180110543.6224.17731 10562.727.2822110577.24 24.117210646.3822.97769
#Mann= 3 , 0 , 0
8071.619  0.0637       08071.619  0.0637       010646.38  0.0637       0
#XS Ineff= 2 , 0
       09202.387        10182.65       0
Bank Sta=8071.619,10646.38
Exp/Cntr=0.3,0.1

Type RM Length L Ch R = 1 ,6320.623,1303.242100,1303.242100,1303.242100
XS GIS Cut Line= 4
390582.743890286 853658.88349754391166.077223637854517.216830883
391463.299445847855400.550164206 391802.18833474855969.994608685
#Sta/Elev= 30
8090.13192.791458121.70889.153878133.79882.533078147.51780.888178182.16266.74665
8218.434 58.39658242.61648.021438378.79615.029588448.159 13.50678544.88519.94968
8752.40223.124289001.47220.279719209.99221.614029294.39925.089019315.50121.21031
 9421.0118.740399463.2149.4899639494.867 20.36669515.96821.232979684.78317.85811
9843.04722.052049959.10720.272719980.20818.2244110001.3110.5569810022.4116.31549
10054.06 19.6498 10193.122.2933510344.3818.7437110623.6721.5402410722.5817.79631
#Mann= 3 , 0 , 0
8090.131  0.0699       08090.131  0.0699       010722.58  0.0699       0
#XS Ineff= 2 , 0
       0 9197.52        10234.42       0
Bank Sta=8090.131,10722.58
Exp/Cntr=0.3,0.1

Type RM Length L Ch R = 1 ,5017.381,267.563200,267.563200,267.563200
XS GIS Cut Line= 6
389736.005029517853907.222915166390194.246449731854568.214821736
390494.877196106855067.152998087390647.910715745855257.502471611
390788.870342615855461.724567695391305.982051693856328.890940025
#Sta/Elev= 30
8525.13774.532818608.19372.914488661.80667.807368679.10763.430648748.31262.12164
8779.75454.972428958.547 49.23748976.27442.26841    899439.115919100.35735.33256
9192.34616.276869628.22415.687969886.72818.161849962.01216.78468 10001.38.511643
10025.6817.6275810102.3919.5288310140.7419.2314410165.8414.8036110585.2417.13467
10866.26 13.048410994.2815.4130511190.8714.8329411202.41 14.672411213.9510.66182
11283.1912.3917411317.8217.0564511332.5321.4616811392.6327.8033911414.63 18.9555
#Mann= 3 , 0 , 0
8525.137  0.0658       08525.137  0.0658       011414.63  0.0658       0
#XS Ineff= 2 , 0
       09796.702        10977.24       0
Bank Sta=8525.137,11414.63
Exp/Cntr=0.3,0.1

Type RM Length L Ch R = 1 ,4749.817,110.501900,110.501900,110.501900
XS GIS Cut Line= 4
 389914.74192906854314.576830684390212.050956843855022.042108483
390661.269706923 855390.96571967391093.127345748 856447.82335851
#Sta/Elev= 30
9110.42752.71228 9240.15   39.799295.287 27.24819306.13421.768499316.98219.65148
9414.60619.83868 9512.2317.542489566.46614.180669920.46117.537819946.34114.72088
9972.2228.40606210008.546.55977910024.2913.6919110071.5618.86135 10276.418.31347
10307.9114.8166310485.0814.2539910548.2917.4084410711.9417.2357411003.6112.20425
 11129.914.3023311241.2711.8005911338.49 13.5517 11360.19.979464 11392.511.12921
11478.93 20.881211500.53 31.112711526.4538.4342111586.9561.1654711600.8164.28496
#Mann= 3 , 0 , 0
9110.427  0.0718       09110.427  0.0718       011600.81  0.0718       0
#XS Ineff= 2 , 0
       09920.584        11100.47       0
Bank Sta=9110.427,11600.81
Exp/Cntr=0.3,0.1

Type RM Length L Ch R = 3 ,4687.736,,,
BEGIN DESCRIPTION:
END DESCRIPTION:
Bridge Culvert--1,0,-1,-1, 0
Deck Dist Width WeirC Skew NumUp NumDn MinLoCord MaxHiCord MaxSubmerge Is_Ogee
40.850950,28.800000,2.6,0, 60, 60, , , 0.95, 0, 0,0,,
 9168.85 9181.29 9192.11 9202.94 9213.76 9246.24 9257.06 9322.01 9355.71 9376.14
 9484.39 9495.21 9527.69 9592.63 9635.93 9657.58 9679.23 9733.36 9765.83 9825.82
 9866.34 9919.05 9975.80 9975.8010024.2010024.2010169.3910281.6210353.8510456.48
10494.2110515.8710570.0010580.8210602.4810905.6210981.4011013.8811037.4511111.32
11165.4511187.1111219.5911306.2011338.6811381.9811392.8111403.6411414.4611425.29
11436.1211457.7711490.2511501.0711511.9011533.5511544.3811566.0311576.8611593.74
   50.64   51.32   49.92   45.00   43.03   43.10   35.09   30.60   24.16   21.55
   20.05   19.00   19.42   21.66   21.79   23.86   27.95   28.16   27.04   23.24
   22.48   19.22   19.76   19.76   18.20   18.20   15.40   14.67   15.62   13.90
   14.01   15.46   16.04   14.49   14.15   14.59   11.88   11.80   13.23   13.95
   13.82   11.99   11.54   13.36   10.10   11.15   14.48   14.64   16.32   19.37
   20.69   30.09   34.37   37.57   45.82   56.08   59.35   67.80   70.76   70.45
 -949.36 -948.68 -950.08 -955.00 -956.97 -956.90 -964.91 -969.40 -975.84 -978.45
 -979.95 -981.00 -980.58 -978.34 -978.21 -976.14 -972.05 -971.84 -972.96 -976.76
 -977.52 -980.78 -980.24   14.76   13.20 -981.80 -984.60 -985.33 -984.38 -986.10
 -985.99 -984.54 -983.96 -985.51 -985.85 -985.41 -988.12 -988.20 -986.77 -986.05
 -986.18 -988.01 -988.46 -986.64 -989.90 -988.85 -985.52 -985.36 -983.68 -980.63
 -979.31 -969.91 -965.63 -962.43 -954.18 -943.92 -940.65 -932.20 -929.24 -929.55
 9168.85 9181.29 9192.11 9202.94 9213.76 9246.24 9257.06 9322.01 9355.71 9376.14
 9484.39 9495.21 9527.69 9592.63 9635.93 9657.58 9679.23 9733.36 9765.83 9825.82
 9866.34 9919.05 9975.80 9975.8010024.2010024.2010169.3910281.6210353.8510456.48
10494.2110515.8710570.0010580.8210602.4810905.6210981.4011013.8811037.4511111.32
11165.4511187.1111219.5911306.2011338.6811381.9811392.8111403.6411414.4611425.29
11436.1211457.7711490.2511501.0711511.9011533.5511544.3811566.0311576.8611593.74
   50.64   51.32   49.92   45.00   43.03   43.10   35.09   30.60   24.16   21.55
   20.05   19.00   19.42   21.66   21.79   23.86   27.95   28.16   27.04   23.24
   22.48   19.22   19.76   19.76   18.20   18.20   15.40   14.67   15.62   13.90
   14.01   15.46   16.04   14.49   14.15   14.59   11.88   11.80   13.23   13.95
   13.82   11.99   11.54   13.36   10.10   11.15   14.48   14.64   16.32   19.37
   20.69   30.09   34.37   37.57   45.82   56.08   59.35   67.80   70.76   70.45
 -949.36 -948.68 -950.08 -955.00 -956.97 -956.90 -964.91 -969.40 -975.84 -978.45
 -979.95 -981.00 -980.58 -978.34 -978.21 -976.14 -972.05 -971.84 -972.96 -976.76
 -977.52 -980.78 -980.24   14.76   13.20 -981.80 -984.60 -985.33 -984.38 -986.10
 -985.99 -984.54 -983.96 -985.51 -985.85 -985.41 -988.12 -988.20 -986.77 -986.05
 -986.18 -988.01 -988.46 -986.64 -989.90 -988.85 -985.52 -985.36 -983.68 -980.63
 -979.31 -969.91 -965.63 -962.43 -954.18 -943.92 -940.65 -932.20 -929.24 -929.55
BR Coef=-1 , 0 , 0 ,, 0 ,,,0.8,0,1,0,
WSPro=,,,, 1 ,,,, 0 ,,,, 0 ,,,,-1 ,-1 ,-1 , 0 , 0 , 0 , 0 , 0
BC Design=,, 0 ,, 0 ,,,,,,

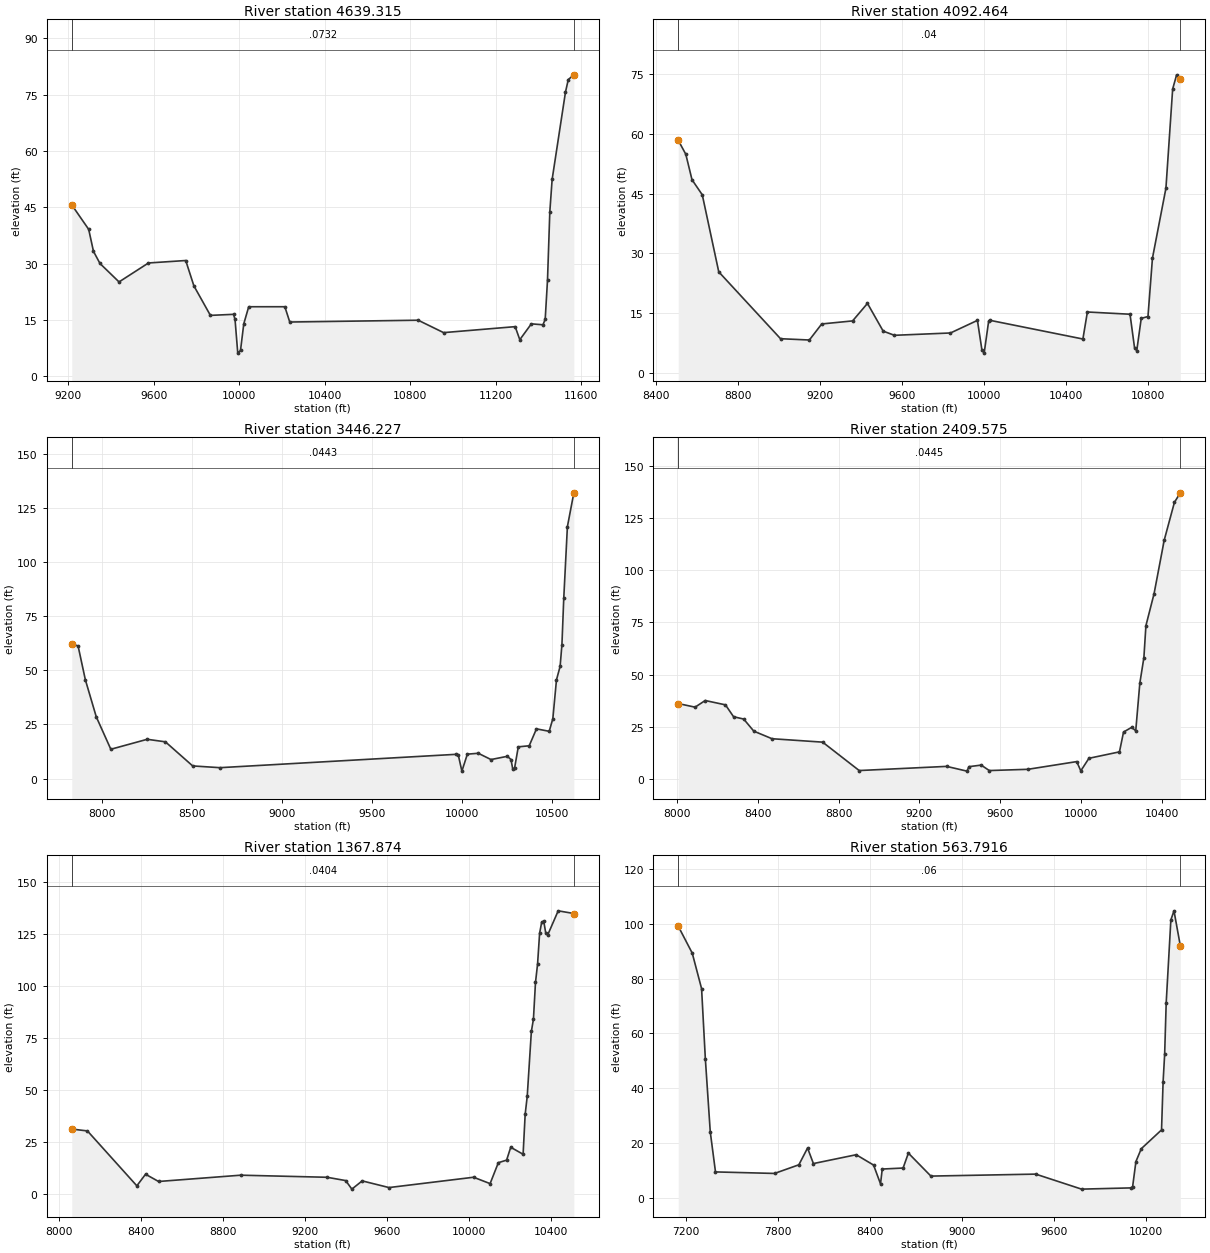
Type RM Length L Ch R = 1 ,4639.315,546.851000,546.851000,546.851000
XS GIS Cut Line= 4
  389825.7662346854514.229608492390105.714151288855071.955302898
390572.294012438855445.219191827390999.811373528856489.055997367
#Sta/Elev= 30
9215.82745.637579295.01239.11209 9317.3933.254489347.86730.012579437.03225.10041
9574.738 30.15359749.11130.80631 9787.3324.046679864.56716.181659972.80516.46218
9979.82315.119859992.6296.11881210005.446.82879510020.83 13.946610043.8518.48359
10212.9218.4880710235.9514.4116410836.9814.8921410955.8411.5841211290.8413.17736
11312.459.69815211366.4813.9236811420.7613.6770311431.3215.1233511442.1225.59751
11452.9343.7928611463.7452.41284 11526.3 75.736511539.3879.0462711565.3780.31028
#Mann= 3 , 0 , 0
9215.827  0.0732       09215.827  0.0732       011565.37  0.0732       0
#XS Ineff= 2 , 0
       09956.445        11041.14       0
Bank Sta=9215.827,11565.37
Exp/Cntr=0.3,0.1

Type RM Length L Ch R = 1 ,4092.464,646.237700,646.237700,646.237700
XS GIS Cut Line= 3
389633.946243372854178.225388018389720.098241982855070.670093332
390352.318266453856489.112608601
#Sta/Elev= 30
8509.89458.38452 8546.8454.870768576.97948.481348627.21244.680288707.58325.32137
9008.9788.5186559149.6298.1907069209.90812.224869360.60512.993259433.12517.39345
9509.76310.424369564.5059.3741949838.2139.9601459969.59313.12397 9991.495.703719
10002.444.89494210024.3312.9073910032.6213.1204710484.178.44181410506.0615.23097
10714.0814.6694510735.986.30851810746.935.51873110768.8213.6225310801.67 14.0971
10823.5628.7655810889.2546.32775 10922.1 71.266510941.4774.8355910959.4573.88306
#Mann= 3 , 0 , 0
8509.894    0.04       08509.894    0.04       010959.45    0.04       0
#XS Ineff= 2 , 0
       09716.186        10437.77       0
Bank Sta=8509.894,10959.45
Exp/Cntr=0.3,0.1

Type RM Length L Ch R = 1 ,3446.227,1036.652100,1036.652100,1036.652100
XS GIS Cut Line= 2
389205.206729183853850.258611146389617.293579742 856610.46719833
#Sta/Elev= 30
7829.36162.365397864.48761.31251 7904.9345.666287965.59528.534898046.48213.54398
8248.69918.154668349.80716.984358501.4695.8377618653.1325.030185 9967.5411.21497
9977.65110.956019997.8723.434611 10028.211.2789510088.8711.6930110159.658.786253
10250.6410.2906510270.868.78966510280.984.20394110291.094.98360510311.3114.66585
10371.9715.1580210412.4222.9845210483.1921.8502310503.4127.6926610523.64 45.6635
10543.8651.8680610553.9761.9926710564.0883.31374 10584.3116.483710620.16132.1364
#Mann= 3 , 0 , 0
7829.361  0.0443       07829.361  0.0443       010620.16  0.0443       0
#XS Ineff= 2 , 0
       09590.336        10132.68       0
Bank Sta=7829.361,10620.16
Exp/Cntr=0.3,0.1

Type RM Length L Ch R = 1 ,2409.575,1041.701000,1041.701000,1041.701000
XS GIS Cut Line= 4
 388648.95307979854061.754265487388697.564190894854825.643154383
388822.564190894 855957.58759883388753.119746476856533.976487726
#Sta/Elev= 30
8006.25536.127228089.66934.39876 8139.7737.582278239.97235.507928280.05329.82646
8330.15528.714448380.256 22.92568470.43819.303968720.94317.667338901.8324.081174
9334.4466.0708489435.0543.8024039445.1155.9327059505.4796.6893989545.7234.076037
9736.8784.6732969978.4148.3604269998.5593.93375910038.85 9.9401410189.9313.01642
10210.0822.5056610250.3724.7473210270.5123.1081610290.6645.82802 10310.858.11113
10320.87 73.397110361.1688.6688610411.52114.330610461.89 132.37110491.07136.9369
#Mann= 3 , 0 , 0
8006.255  0.0445       08006.255  0.0445       010491.07  0.0445       0
#XS Ineff= 2 , 0
       09643.678                       0
Bank Sta=8006.255,10491.07
Exp/Cntr=0.3,0.1

Type RM Length L Ch R = 1 ,1367.874,804.082000,804.082000,804.082000
XS GIS Cut Line= 3
388274.825841129854057.580302939387851.214730024854849.246969581
388031.770285547856390.913636267
#Sta/Elev= 30
 8060.9631.365958137.42530.462338378.5274.1474198420.9659.7040068484.5066.227049
 8885.979.2495559306.9538.2420299397.5686.6651279427.7732.5633599478.1156.512846
9609.0033.31453810021.818.25855210102.355.20526710142.63 15.2422 10182.916.46451
10203.0422.6317310263.4519.2773110273.5138.4331810283.5847.0867810303.7278.17908
10313.7983.9836310323.86 101.65110333.92110.368510343.99125.238110354.06130.5067
10364.13131.0094 10374.2125.205410384.27 124.60710434.61 135.99410511.04134.7088
#Mann= 3 , 0 , 0
 8060.96  0.0404       0 8060.96  0.0404       010511.04  0.0404       0
#XS Ineff= 2 , 0
       09779.244                       0
Bank Sta=8060.96,10511.04
Exp/Cntr=0.3,0.1

Type RM Length L Ch R = 1 ,563.7916,204.761100,204.761100,204.761100
XS GIS Cut Line= 4
385692.230354995853860.583775163386780.772021651855912.667108476
387413.584521651856160.062941805387457.855355024856425.687941819
#Sta/Elev= 30
7150.02899.192977241.29789.351397302.18576.365117326.65750.737637358.78423.99606
7392.7439.3875277777.6188.8305917936.09511.991997992.69418.119938030.869 12.4419
8309.64915.669518422.84811.891658468.1275.0289998479.44710.438698615.28510.80477
8649.722 16.25568796.4027.8635519479.3588.5839349778.127 3.0979110100.243.546621
10111.034.03656510132.4513.1855610167.5517.8833110299.3424.7396710309.4842.25285
10319.62 52.339110329.7571.2107510360.17101.489710380.44104.806310421.6992.05562
#Mann= 3 , 0 , 0
7150.028    0.06       07150.028    0.06       010421.69    0.06       0
#XS Ineff= 2 , 0
       0 9758.23                       0
Bank Sta=7150.028,10421.69
Exp/Cntr=0.3,0.1

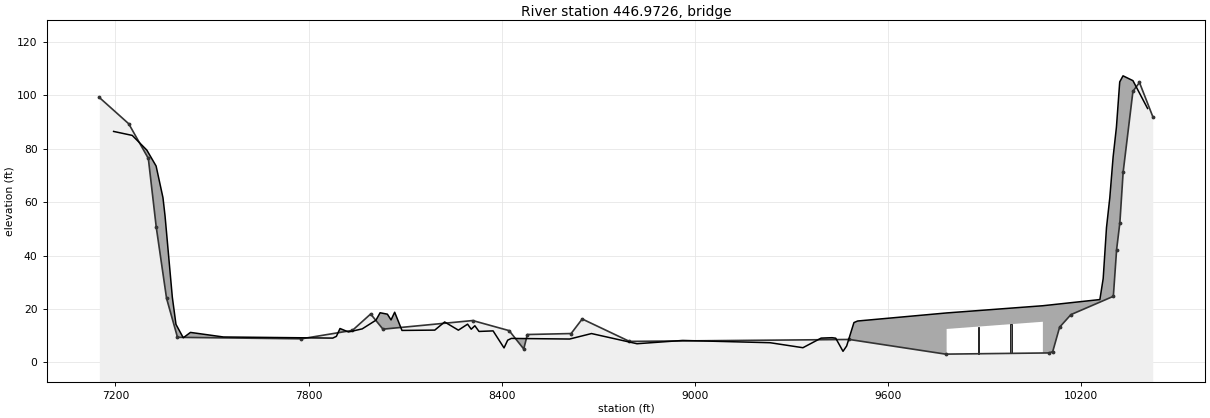
Type RM Length L Ch R = 3 ,446.9726,,,
BEGIN DESCRIPTION:
END DESCRIPTION:
Bridge Culvert--1,0,-1,-1, 0
Deck Dist Width WeirC Skew NumUp NumDn MinLoCord MaxHiCord MaxSubmerge Is_Ogee
67.767750,69.225600,2.6,0, 60, 60, , , 0.95, 0, 0,0,,
 7194.37 7252.24 7297.52 7326.33 7347.67 7354.12 7376.76 7388.08 7410.73 7433.02
 7535.25 7874.86 7886.18 7897.50 7923.76 7966.43 8009.10 8022.02 8044.66 8055.98
 8067.30 8089.94 8191.83 8222.47 8265.14 8293.71 8305.03 8316.35 8329.15 8372.95
 8406.91 8418.23 8429.55 8610.68 8678.60 8819.90 8961.61 9233.29 9335.18 9391.78
 9425.74 9437.06 9459.70 9471.02 9493.66 9504.98 9781.56 9781.5610080.4410080.44
10257.4910267.7710278.0410288.3110298.5810308.8610319.1310329.4010360.2210405.64
   86.48   84.99   79.49   73.53   61.67   54.83   24.37   14.22    9.22   11.23
    9.52    9.10    9.74   12.69   11.39   12.55   15.80   18.59   18.06   15.90
   18.79   11.97   12.09   15.14   12.07   14.31   12.43   13.72   11.59   11.80
    5.42    8.32    8.98    8.75   10.80    6.99    8.22    7.37    5.50    9.10
    9.25    9.07    4.15    6.14   14.91   15.50   18.52   18.52   21.22   21.22
   23.53   31.40   50.49   61.66   76.89   88.06  105.03  107.30  105.49   95.08
 -913.52 -915.01 -920.51 -926.47 -938.33 -945.17 -975.63 -985.78 -990.78 -988.77
 -990.48 -990.90 -990.26 -987.31 -988.61 -987.45 -984.20 -981.41 -981.94 -984.10
 -981.21 -988.03 -987.91 -984.86 -987.93 -985.69 -987.57 -986.28 -988.41 -988.20
 -994.58 -991.68 -991.02 -991.25 -989.20 -993.01 -991.78 -992.63 -994.50 -990.90
 -990.75 -990.93 -995.85 -993.86 -985.09 -984.50 -981.48   12.52   15.22 -978.78
 -976.47 -968.60 -949.51 -938.34 -923.11 -911.94 -894.97 -892.70 -894.51 -904.92
 7194.37 7252.24 7297.52 7326.33 7347.67 7354.12 7376.76 7388.08 7410.73 7433.02
 7535.25 7874.86 7886.18 7897.50 7923.76 7966.43 8009.10 8022.02 8044.66 8055.98
 8067.30 8089.94 8191.83 8222.47 8265.14 8293.71 8305.03 8316.35 8329.15 8372.95
 8406.91 8418.23 8429.55 8610.68 8678.60 8819.90 8961.61 9233.29 9335.18 9391.78
 9425.74 9437.06 9459.70 9471.02 9493.66 9504.98 9861.86 9861.8610160.7510160.75
10257.4910267.7710278.0410288.3110298.5810308.8610319.1310329.4010360.2210405.64
   86.48   84.99   79.49   73.53   61.67   54.83   24.37   14.22    9.22   11.23
    9.52    9.10    9.74   12.69   11.39   12.55   15.80   18.59   18.06   15.90
   18.79   11.97   12.09   15.14   12.07   14.31   12.43   13.72   11.59   11.80
    5.42    8.32    8.98    8.75   10.80    6.99    8.22    7.37    5.50    9.10
    9.25    9.07    4.15    6.14   14.91   15.50   19.32   19.32   22.53   22.53
   23.53   31.40   50.49   61.66   76.89   88.06  105.03  107.30  105.49   95.08
 -913.52 -915.01 -920.51 -926.47 -938.33 -945.17 -975.63 -985.78 -990.78 -988.77
 -990.48 -990.90 -990.26 -987.31 -988.61 -987.45 -984.20 -981.41 -981.94 -984.10
 -981.21 -988.03 -987.91 -984.86 -987.93 -985.69 -987.57 -986.28 -988.41 -988.20
 -994.58 -991.68 -991.02 -991.25 -989.20 -993.01 -991.78 -992.63 -994.50 -990.90
 -990.75 -990.93 -995.85 -993.86 -985.09 -984.50 -980.68   13.32   16.53 -977.47
 -976.47 -968.60 -949.51 -938.34 -923.11 -911.94 -894.97 -892.70 -894.51 -904.92
Pier Skew, UpSta & Num, DnSta & Num=  ,9880.52, 2 ,9960.83, 2 , 0 , 0 , 0 ,,
    4.00    4.00
 -980.52   19.48
    4.00    4.00
 -979.82   20.18
Pier Skew, UpSta & Num, DnSta & Num=  ,9981.48, 2 ,10061.79, 2 , 0 , 0 , 0 ,,
    4.00    4.00
 -979.64   20.36
    4.00    4.00
 -978.94   21.06
BR Coef=-1 , 0 , 0 ,, 0 ,,,0.8,0,1,0,
WSPro=,,,, 1 ,,,, 0 ,,,, 0 ,,,,-1 ,-1 ,-1 , 0 , 0 , 0 , 0 , 0
BC Design=,, 0 ,, 0 ,,,,,,