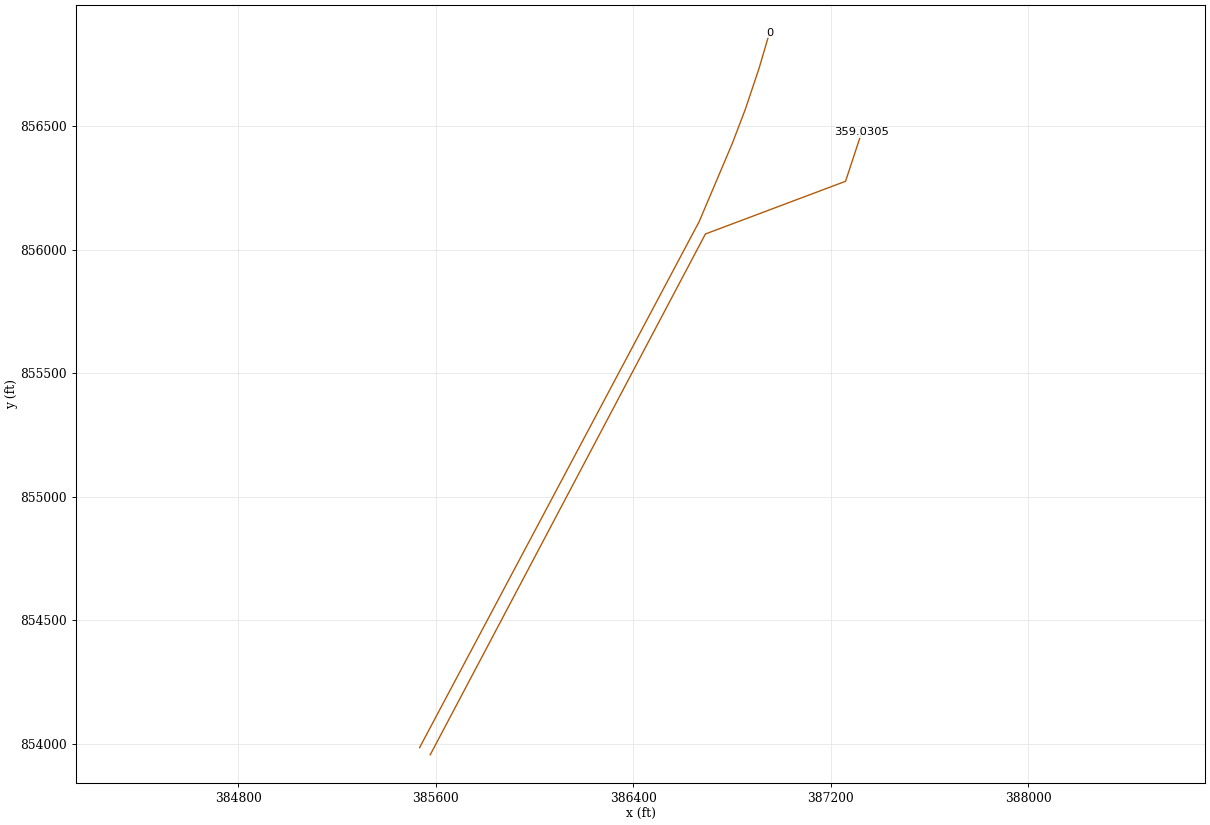
HEC-RAS study 6977_ras.prj: 6977

--- 6977_ras.g01 (geometry) --- (continued)

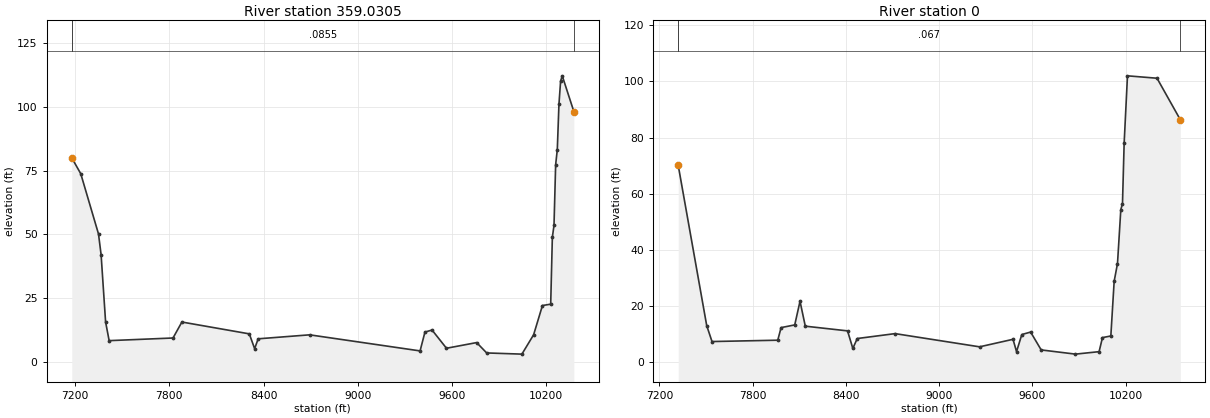
Type RM Length L Ch R = 1 ,359.0305,359.030500,359.030500,359.030500
XS GIS Cut Line= 4
385577.647021681853954.333775163386692.230355024856063.708775148
387259.938688308856277.250441819387325.042855024856475.167108476
#Sta/Elev= 30
7177.60579.97495 7234.9173.737867348.01250.104247364.58341.959277393.25215.55777
7415.8738.2442187823.0399.284068 7879.59 15.55028309.37710.906628343.3075.104267
8365.9288.9648148693.92310.525339398.0364.2149449429.08411.617559474.32512.40876
9566.305 5.259319758.6187.4861089822.6493.41825610047.092.95395710121.8810.56281
10178.05 22.025510230.6822.5576210241.2148.7949410251.7453.4599410262.2677.27934
10272.7983.1979610283.32101.020810293.84110.072910304.37112.156110378.2498.14017
#Mann= 3 , 0 , 0
7177.605  0.0855       07177.605  0.0855       010378.24  0.0855       0
#XS Ineff= 2 , 0
       09877.411                       0
Bank Sta=7177.605,10378.24
Exp/Cntr=0.3,0.1

Type RM Length L Ch R = 1 ,       0,0.000000,0.000000,0.000000
XS GIS Cut Line= 6
 385534.45270893853983.188774049386666.935756326856113.865326434
386801.916044831856432.505468935386854.063667178856569.238396153
386909.310084015856734.065192923386951.794501722856878.787474468
#Sta/Elev= 30
7320.97770.125657504.224 13.10137538.1997.4461797961.3437.924027 7982.6512.40434
8070.46313.365418104.43821.777738138.41212.915988410.20711.240328444.181 4.99265
8472.7038.5198368715.97610.265839259.5655.5648849474.7368.2429529497.3863.856592
 9531.369.9449719587.98410.815769655.9334.4637079876.4182.96740710028.483.843666
10050.168.84845410104.059.42435910125.4528.9023210146.8635.1964310168.26 54.4234
10178.9756.4963210189.67 78.011310211.07102.012310401.13101.157310550.9986.39788
#Mann= 3 , 0 , 0
7320.977   0.067       07320.977   0.067       010550.99   0.067       0
#XS Ineff= 2 , 0
       09743.548                       0
Bank Sta=7320.977,10550.99
Exp/Cntr=0.3,0.1